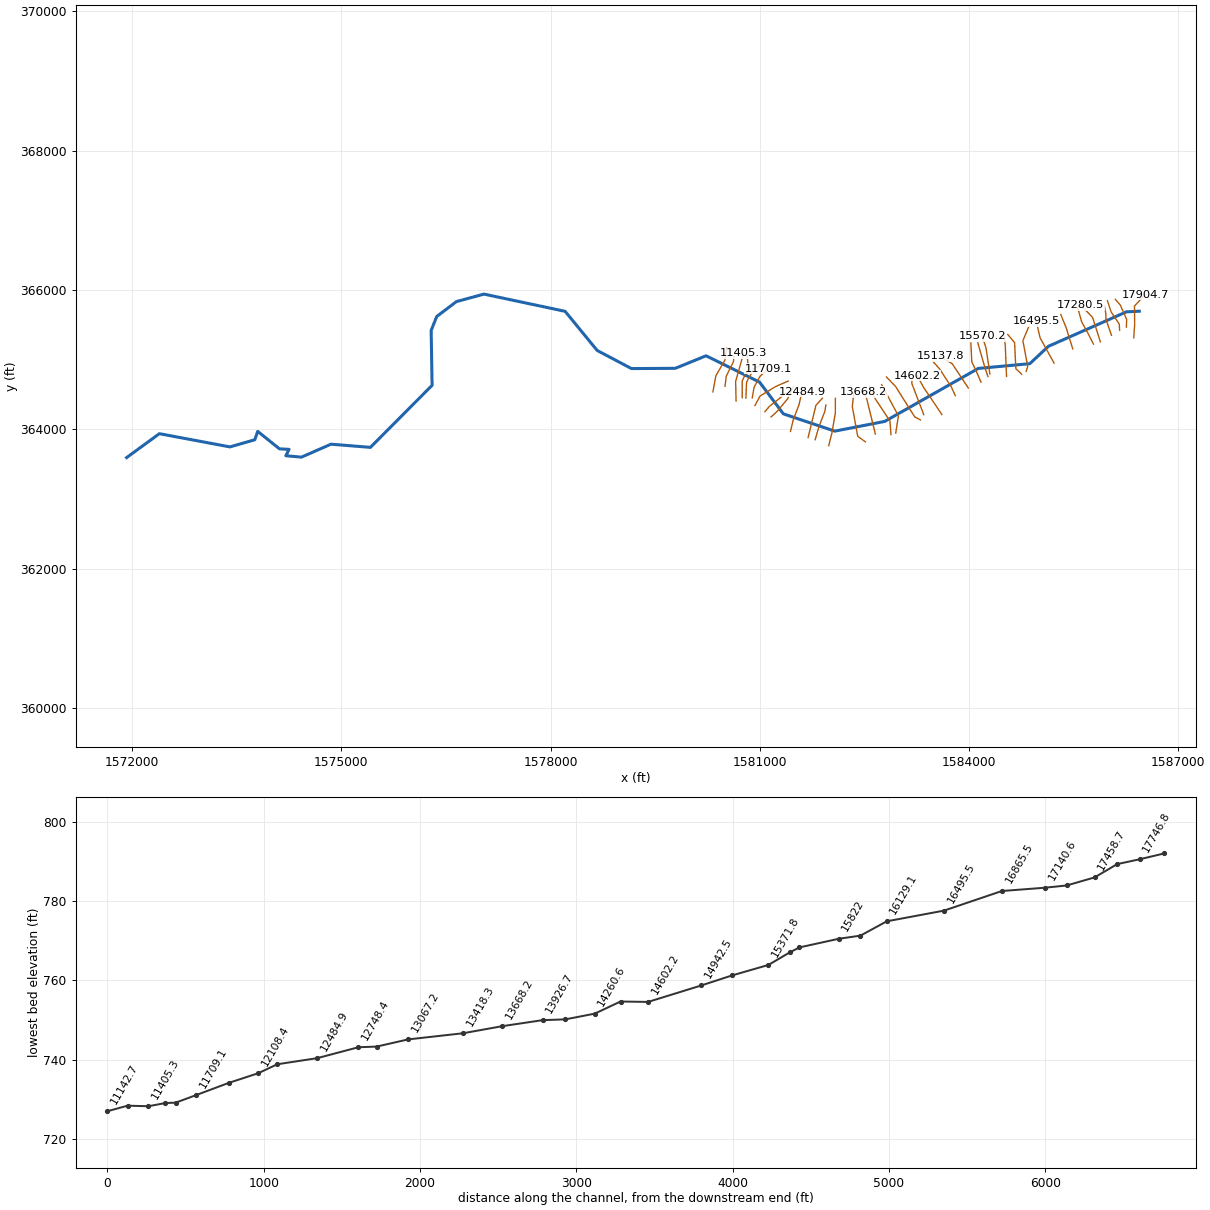
--- GORRLRN1.prj (project) ---

Proj Title=GORRLRN1
Current Plan=p01
Default Exp/Contr=0,0
English Units
Geom File=g01
Flow File=f01
Plan File=p01
BEGIN DESCRIPTION:
END DESCRIPTION:
DSS Export Rating Curves= 0
DSS Export Rating Curve Sorted= 0
DSS Export Volume Flow Curves= 0
DXF OffsetX= 0
DXF OffsetY= 0
DXF ScaleX= 0
DXF ScaleY= 0

--- GORRLRN1.p01 (plan) ---

Plan Title=Floodplain
Program Version=4.00
Geom File=g01
Flow File=f01
K Sum by GR=0
Std Step Tol=0.01
Critical Tol=0.01
Num of Std Step Trials=20
Max Error Tol=0.3
Flow Tol Ratio=0.001
Split Flow NTrial=30
Split Flow Tol=0.02
Split Flow Ratio=0.02
Log Output Level=0
Friction Slope Method=1
Unsteady Friction Slope Method=2
Unsteady Bridges Friction Slope Method=1
Global Log Level=0
CheckData=False
Run HTab=0
Run UNet=0
Run PostProcess=0
UNET Theta=0
UNET Theta Warmup=0
UNET ZTol=0
UNET ZSATol=0
UNET MxIter=0
UNET MaxInSteps=0
UNET DtIC=0
UNET DtMin=0
UNET MaxCRTS=0
UNET WFStab=0
UNET SFStab=0
UNET WFX=0
UNET SFX=0
UNET DSS MLevel=0
UNET DZMax Abort=0
UNET Convert EG Bridges=0
UNET Use Existing IB Tables=0
UNET Froude Limit=0
UNET Froude Power=0
Write IC File=0
Echo Input=False
Echo Output=False
Write Detailed=0

--- GORRLRN1.f01 (steady flow) ---

Flow Title=NFF Regression Equation
Program Version=4.10
Number of Profiles= 1
Profile Names=P100yr
River Rch & RM=GORRLRN1,Main            ,17904.7
793.1783
River Rch & RM=GORRLRN1,Main            ,17603.1
917.1558
River Rch & RM=GORRLRN1,Main            ,15137.8
969.6721
River Rch & RM=GORRLRN1,Main            ,14942.5
1100.108
River Rch & RM=GORRLRN1,Main            ,12865.6
1175.933
River Rch & RM=GORRLRN1,Main            ,9975.6
1293.302
River Rch & RM=GORRLRN1,Main            ,6692.2
1393.365
River Rch & RM=GORRLRN1,Main            ,506.6
1527.509
Boundary for River Rch & Prof#=GORRLRN1,Main            , 1
Up Type= 0
Dn Type= 3
Dn Slope=0.0165
DSS Import GetInterval= 0
DSS Import GetPeak= 0
DSS Import FillOption= 0

--- GORRLRN1.g01 (geometry) ---

Geom Title=USGS 10m DEM
Program Version=4.10

River Reach=GORRLRN1        ,Main
Reach XY= 30
     1586443.146      365695.286     1586258.683      365686.393
     1585139.781      365191.517     1584872.493      364941.849
     1584135.071      364874.151     1582791.934      364113.078
     1582075.841      363973.567     1581338.675      364221.643
     1580996.804      364677.424     1580230.088      365055.345
     1579788.685      364875.313     1579159.788      364871.883
     1578667.861      365131.995     1578208.356      365693.662
     1577044.876      365940.991     1576649.954      365833.569
     1576367.657      365619.901      1576287.28      365419.064
     1576300.557       364631.26     1575416.264      363740.626
     1574850.683      363786.069     1574427.441      363600.631
     1574203.263      363620.247       1574249.8      363712.089
     1574112.105      363719.359       1573799.8      363969.784
     1573757.865      363850.077     1573401.623      363747.238
      1572389.43      363936.974     1571919.251      363593.506

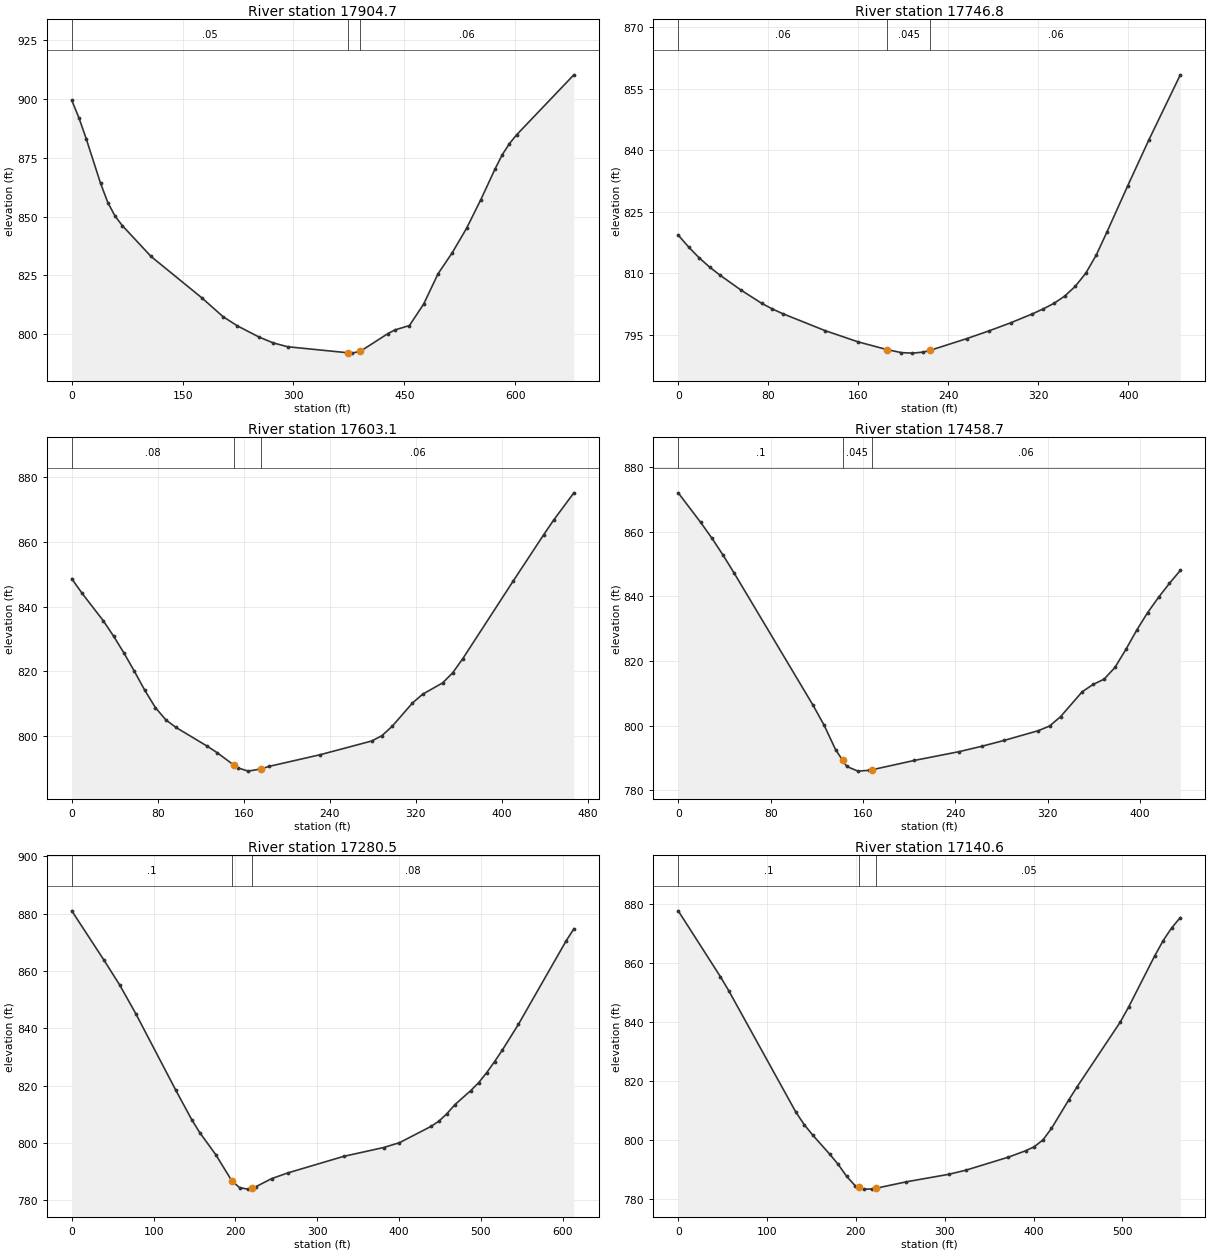
Type RM Length L Ch R = 1 ,17904.7 ,148.5,157.9,166.8
XS GIS Cut Line= 4
     1586363.566      365313.962     1586376.841      365508.658
     1586374.096       365770.37      1586526.24      365932.712
#Sta/Elev= 30
       0  899.54     9.8  891.99    19.5  883.24      39  864.17    48.8  856.03
    58.5  850.32    68.3  846.26   107.3  833.09   175.6  815.59   204.8  807.46
   224.2  803.55   253.3  798.82   272.7   796.3   292.1  794.68   373.5 792.115
   379.3  791.96   390.7  792.78   427.8  800.27   437.5  801.85   456.9   803.7
   476.2  812.86   495.6  825.71   514.9  834.71   534.3  845.12   553.6  857.33
     573  870.47   582.6  876.42   592.3  881.15     602  884.87   679.4  910.38
#Mann= 3 , 0 , 0
       0     .05       0   373.5    .045       0   390.7     .06       0
Bank Sta=373.5,390.7
XS Rating Curve= 0 ,0
Exp/Cntr=0.3,0.1

Type RM Length L Ch R = 1 ,17746.8 ,139.7,143.7,147.5
XS GIS Cut Line= 4
     1586257.978      365466.705     1586262.145      365577.816
     1586171.937      365781.706      1586098.95      365866.705
#Sta/Elev= 30
       0  819.27     9.3  816.35    18.5  813.75    27.8  811.49    37.1   809.5
    55.6  805.89    74.1  802.64    83.4  801.29    92.7  800.12   130.6  795.96
   159.7  793.24   185.4 791.351   198.4   790.6   208.1  790.48   217.8  790.73
   224.1 791.179   256.6  794.04     276  795.89   295.4  797.87   314.8  800.06
   324.4  801.27   334.1  802.65   343.5   804.4   352.8  806.76   362.2  809.98
   371.5   814.4   380.8  819.91   399.5  831.32   418.2  842.46   446.2  858.36
#Mann= 3 , 0 , 0
       0     .06       0   185.4    .045       0   224.1     .06       0
Bank Sta=185.4,224.1
XS Rating Curve= 0 ,0
Exp/Cntr=0.3,0.1

Type RM Length L Ch R = 1 ,17603.1 ,149.7,144.4,138.3
XS GIS Cut Line= 4
     1586160.756      365422.261     1586156.109      365509.609
     1586039.377      365684.926      1585986.45      365845.177
#Sta/Elev= 30
       0  848.59     9.7  844.06    29.2  835.69    38.9  830.89    48.6  825.66
    58.3  820.01      68  814.14    77.8  808.84    87.5  805.07      97  802.72
   125.8  796.99   135.3  794.93   150.8 791.099   154.3  790.28   164.1  789.26
   175.8 789.935   183.2   790.7   231.1  794.33     279  798.56   288.5  800.22
   298.1  803.14   316.8  810.26   326.2  812.96     345   816.5   354.4  819.66
   363.7  823.99   410.6  847.94   438.7  862.09   448.1  866.68   466.9  875.09
#Mann= 3 , 0 , 0
       0     .08       0   150.8    .045       0   175.8     .06       0
Bank Sta=150.8,175.8
XS Rating Curve= 0 ,0
Exp/Cntr=0.3,0.1

Type RM Length L Ch R = 1 ,17458.7 ,178.7,178.2,177.5
XS GIS Cut Line= 4
     1586044.089      365349.517     1585964.651      365579.338
     1585964.108       365657.69     1585942.353      365768.788
#Sta/Elev= 30
       0  872.03    19.4  862.89    29.2  857.97    38.9   852.7    48.6  847.09
   116.7  806.31   126.4  800.06   136.2  792.58   142.3 789.297   145.9  787.36
   155.6  785.91   165.4  786.16   167.7 786.328   204.3  789.21   243.2  791.94
   262.8   793.6   282.3  795.43   311.7  798.42   321.5  799.87     331  802.76
   349.8  810.49   359.2  812.73   368.7  814.37   378.1  817.99   387.6  823.59
     397  829.56   406.4  834.96   415.9  839.72   425.3  844.02   434.7  848.03
#Mann= 3 , 0 , 0
       0      .1       0   142.3    .045       0   167.7     .06       0
Bank Sta=142.3,167.7
XS Rating Curve= 0 ,0
Exp/Cntr=0.3,0.1

Type RM Length L Ch R = 1 ,17280.5 ,135.3,139.9,144.2
XS GIS Cut Line= 3
     1585885.306      365254.805     1585772.459      365608.538
     1585602.542      365781.084
#Sta/Elev= 30
       0  880.98    39.1  863.89    58.6  855.09    78.2  845.12     127  818.46
   146.6  808.11   156.3  803.63   175.9  795.93   195.4  786.86     205  784.41
     215  783.88   220.8 784.364   224.7  784.69   244.3  787.55   263.8  789.52
   332.2  795.31     381  798.39   400.4  800.08   439.1  805.78   448.8  807.64
   458.5  810.24   468.2  813.37   487.5  818.25   497.2  821.03   506.9   824.5
   516.6  828.35   526.3  832.48   545.7  841.35   603.8  870.36   613.5  874.72
#Mann= 3 , 0 , 0
       0      .1       0   195.4    .045       0   220.8     .08       0
Bank Sta=195.4,220.8
XS Rating Curve= 0 ,0
Exp/Cntr=0.3,0.1

Type RM Length L Ch R = 1 ,17140.6 ,279.5,275.1,270.4
XS GIS Cut Line= 4
     1585785.914      365222.947     1585704.533      365383.494
     1585616.643      365542.999     1585561.434      365738.572
#Sta/Elev= 30
       0  877.56    47.4   855.3    56.8  850.55   132.6  809.31   142.1  805.05
   151.6  801.55   170.5  795.17     180  791.73   189.6  787.66   199.2  784.47
   203.2  783.99   208.8  783.31   218.3  783.36   223.2  783.64   256.7  785.78
   304.6  788.33   323.8  789.72   371.8  794.15   391.1   796.3   400.8  797.66
   410.5  799.94   420.2  803.85   439.5  813.44   449.2  818.01   497.6  839.85
   507.3   845.1   536.3  862.21     546  867.49   555.6   871.8   565.3  875.28
#Mann= 3 , 0 , 0
       0      .1       0   203.2    .045       0   223.2     .05       0
Bank Sta=203.2,223.2
XS Rating Curve= 0 ,0
Exp/Cntr=0.3,0.1

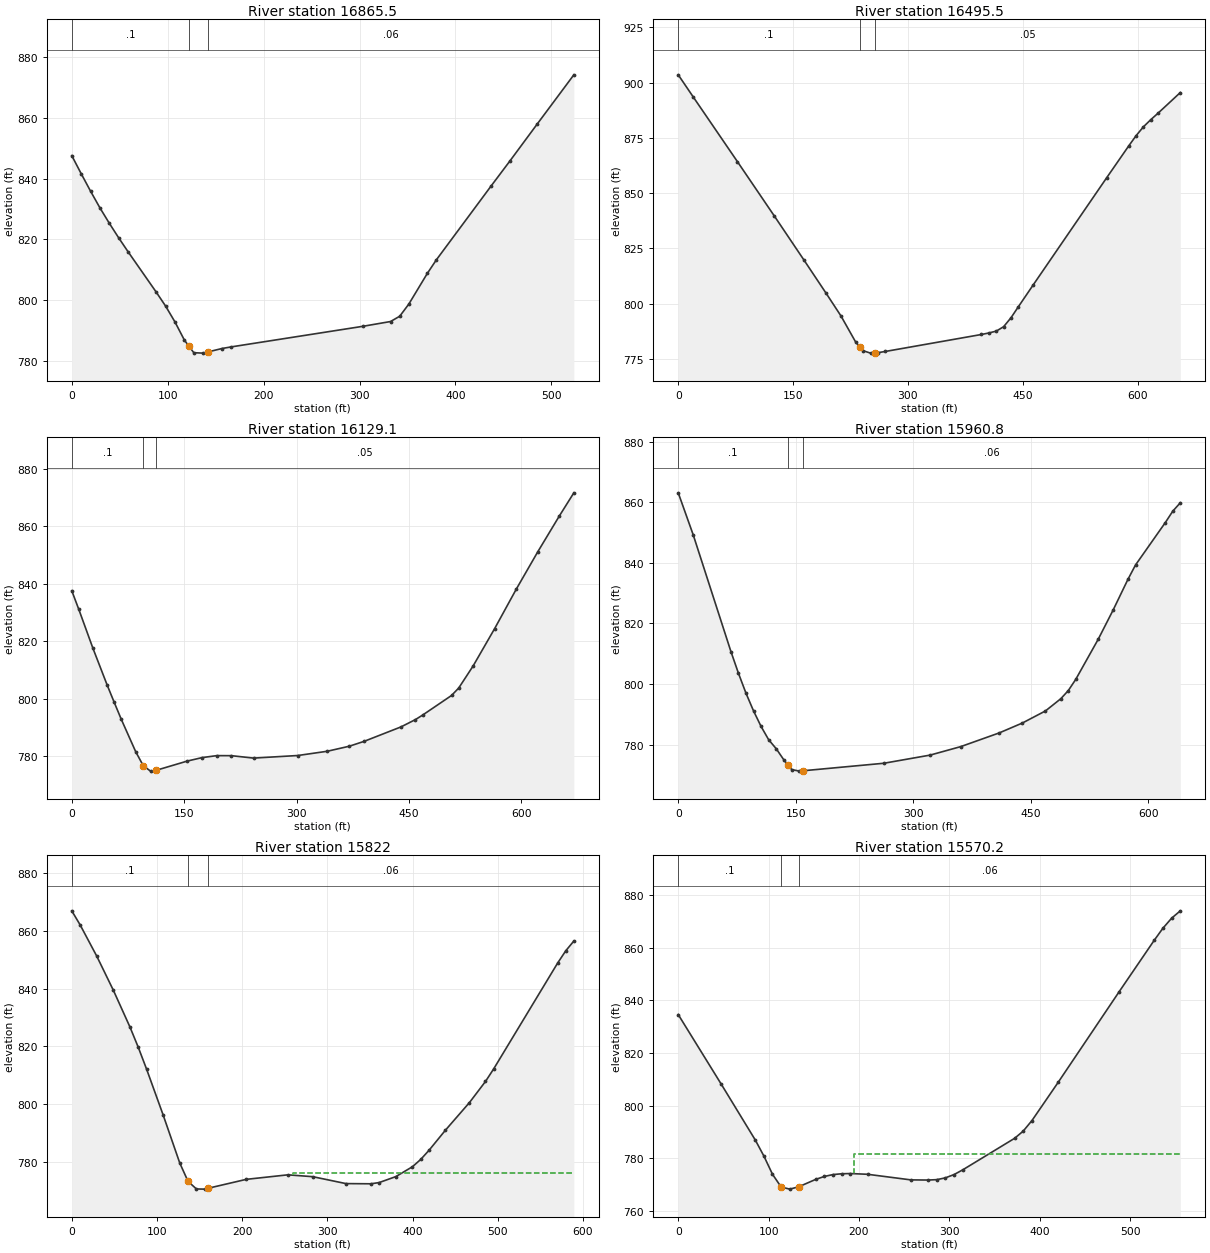
Type RM Length L Ch R = 1 ,16865.5 ,365.1,370,374.2
XS GIS Cut Line= 3
     1585489.228      365153.337     1585393.337       365461.53
     1585317.353      365647.261
#Sta/Elev= 27
       0  847.61     9.8  841.66    19.6  835.88    29.3  830.41    39.1  825.32
    48.9   820.5    58.7  815.91      88  802.62    97.8     798   107.6  792.75
   117.4  786.78   122.1  784.78   127.2  782.62   136.9  782.48   142.1  782.88
   156.5     784   166.3  784.54   303.2  791.31   332.3   792.9   341.9  794.65
   351.4  798.67   370.6  808.74   380.1  813.25   437.4   837.7   456.6  845.78
   485.2  858.02   523.4  874.25
#Mann= 3 , 0 , 0
       0      .1       0   122.1    .045       0   142.1     .06       0
Bank Sta=122.1,142.1
XS Rating Curve= 0 ,0
Exp/Cntr=0.3,0.1

Type RM Length L Ch R = 1 ,16495.5 ,373.5,366.4,358.7
XS GIS Cut Line= 3
     1585220.596      364950.649     1585019.931      365314.243
     1584965.362       365548.36
#Sta/Elev= 28
       0  903.53    19.3  893.66    77.3  864.23   125.6  839.57   164.2  819.68
   193.2  804.61   212.5  794.38   231.8  782.51   236.9 780.454   241.4  778.64
   251.1  777.54   257.4 777.676   260.8  777.75   270.4  778.29     396  785.98
   405.6  786.66   415.3   787.5   424.9  789.49   434.5  793.52   444.1  798.49
   463.4  808.33   559.5  856.92   588.4  871.38     598     876   607.6  880.02
   617.2  883.25   626.8  886.22   655.7  895.51
#Mann= 3 , 0 , 0
       0      .1       0   236.9    .045       0   257.4     .05       0
Bank Sta=236.9,257.4
XS Rating Curve= 0 ,0
Exp/Cntr=0.3,0.1

Type RM Length L Ch R = 1 ,16129.1 ,171.3,168.3,165.1
XS GIS Cut Line= 4
     1584820.571      364831.577     1584842.793      364903.799
     1584773.522      365270.987     1584858.592       365474.98
#Sta/Elev= 30
       0  837.57     9.4  831.07    28.3  817.52    47.2   804.8    56.7  798.73
    66.1  792.85    85.4  781.56    95.4  776.74   105.1  774.84   112.4 775.108
   154.2  778.34   173.9  779.54   193.6  780.23   213.2  780.21   242.7  779.37
   301.7  780.27   341.1  781.75   370.6  783.51   390.2  785.19   439.4  790.21
   458.8  792.77   468.4  794.34   506.9  801.14   516.5  803.73   535.7  811.39
   564.5  824.41   593.4  838.14   622.2  851.17     651  863.63   670.2  871.61
#Mann= 3 , 0 , 0
       0      .1       0    95.4    .045       0   112.4     .05       0
Bank Sta=95.4,112.4
XS Rating Curve= 0 ,0
Exp/Cntr=0.3,0.1

Type RM Length L Ch R = 1 ,15960.8 ,138.5,138.8,138.2
XS GIS Cut Line= 4
     1584755.423      364790.886     1584672.524      364871.181
     1584654.837      365243.767     1584557.181      365360.954
#Sta/Elev= 30
       0  863.08    19.2  849.15    67.3  810.67    76.9  803.51    86.6  796.88
    96.2  791.07   105.8  785.96   115.4  781.61   125.2  778.59     135  774.88
   140.1  773.26   144.9  771.74   154.7  771.23   159.1 771.342   262.6  773.83
   321.6  776.52   360.8  779.33   409.9  783.85   439.3   787.1   468.8  791.09
   488.4  795.12     498  797.82   507.5  801.51   536.1  814.71   555.2  824.38
   574.2  834.56   583.8  839.26   621.9  853.28   631.4  857.03     641   859.8
#Mann= 3 , 0 , 0
       0      .1       0   140.1    .045       0   159.1     .06       0
Bank Sta=140.1,159.1
XS Rating Curve= 0 ,0
Exp/Cntr=0.3,0.1

Type RM Length L Ch R = 1 ,15822   ,249.1,251.7,254.1
XS GIS Cut Line= 3
     1584539.001      364759.399     1584521.941      365188.182
     1584505.928      365347.541
#Sta/Elev= 30
       0  866.99     9.8  862.12    29.3  851.28    48.8  839.44    68.3  826.68
      78  819.68    87.8  812.08   107.3  796.12   126.8  779.46   136.5  773.12
   146.3   770.5     156  770.44   159.9  770.73   204.8  773.83   253.6   775.4
   282.8  774.76   321.8  772.36   351.1  772.29   360.8  772.72   380.4  774.79
   399.9  778.22   409.6  780.75   419.4  783.94   438.5  790.86   466.8  800.48
   485.6   807.8   495.1   812.1   570.4  848.93   579.9  853.16   589.3  856.51
#Mann= 3 , 0 , 0
       0      .1       0   136.5    .045       0   159.9     .06       0
#XS Ineff= 2 , 0
       0                     260       0     776
Permanent Ineff=
       F       F
Bank Sta=136.5,159.9
XS Rating Curve= 0 ,0
Exp/Cntr=0.3,0.1

Type RM Length L Ch R = 1 ,15570.2 ,56.9,60.2,62.9
XS GIS Cut Line= 4
     1584298.979      364795.218      1584286.95      364889.205
     1584243.829      365172.921     1584188.864      365337.901
#Sta/Elev= 30
       0  834.58    47.4  808.25    85.3   786.9    94.8  780.82   104.3  773.91
   113.6 769.202   113.9  769.05   123.4  768.26   133.3 769.145   152.2  771.97
   161.7  773.08   171.3  773.79   180.8   774.1   190.4  774.18   209.5   773.9
   257.4  771.77   276.5  771.71   286.1  771.86   295.6  772.54   305.2  773.79
   314.8  775.58   372.2  787.56   381.7  790.29   391.4   794.3   420.4  808.82
     488  843.31   526.6  862.74   536.3  867.37     546  871.21   555.6     874
#Mann= 3 , 0 , 0
       0      .1       0   113.6    .045       0   133.3     .06       0
#XS Ineff= 2 , 0
                          194.51          781.73
Permanent Ineff=
       F       F
Bank Sta=113.6,133.3
XS Rating Curve= 0 ,0
Exp/Cntr=0.3,0.1

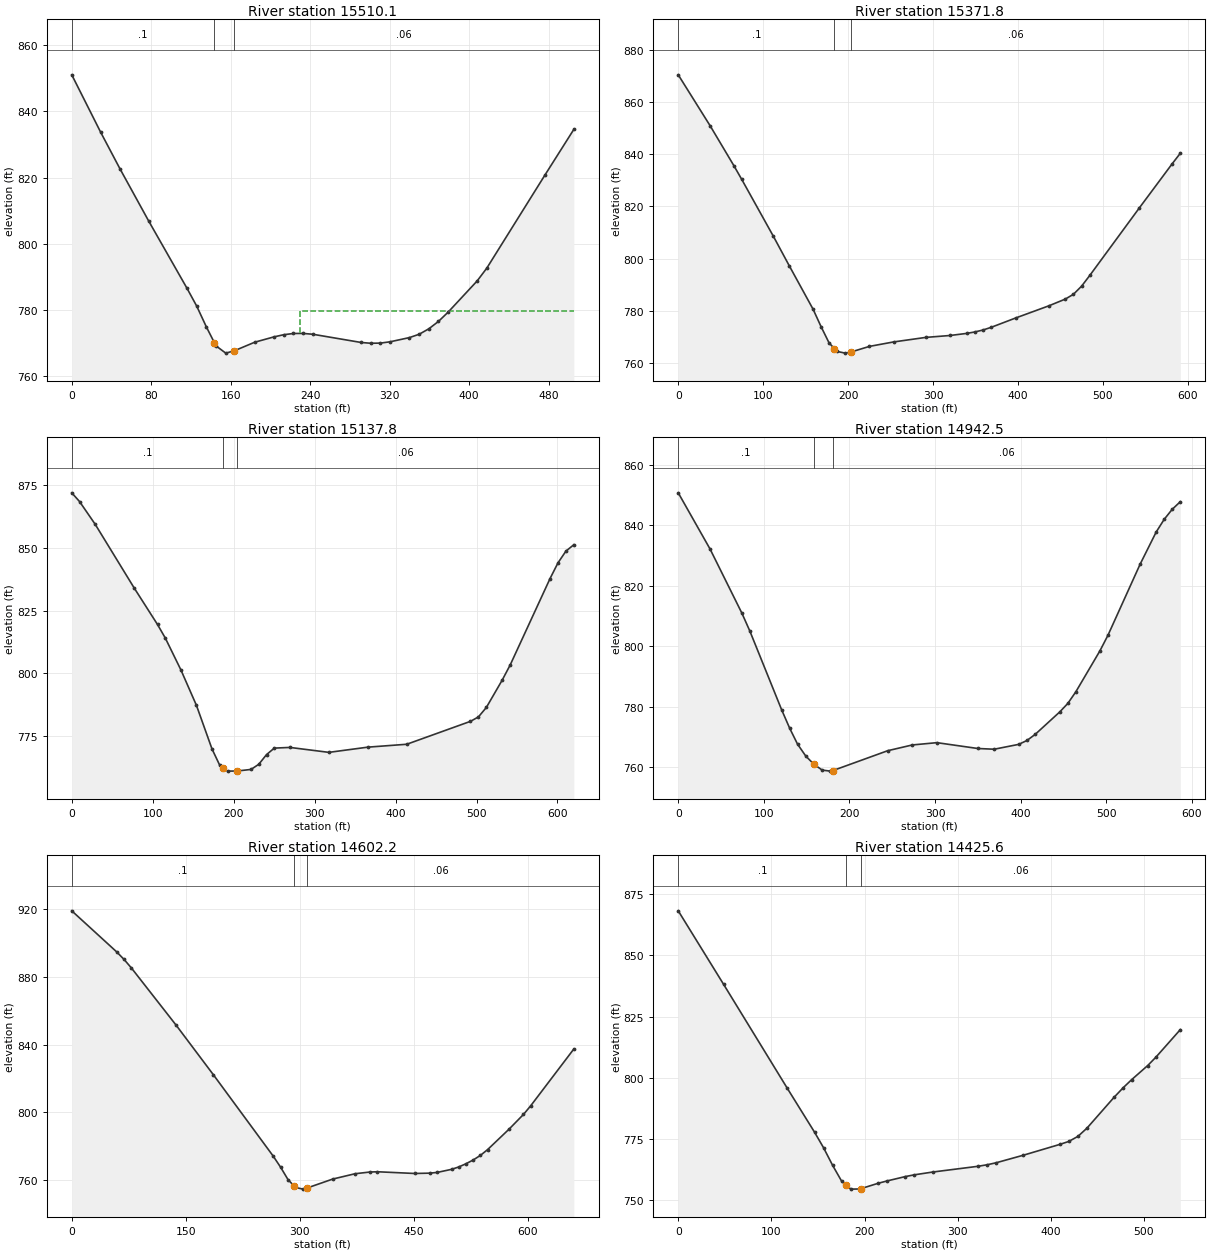
Type RM Length L Ch R = 1 ,15510.1 ,134.5,138.3,141.8
XS GIS Cut Line= 3
     1584272.111      364757.699     1584229.056      364886.171
     1584126.973      365241.727
#Sta/Elev= 30
       0  851.07      29  833.79    48.4  822.76    77.4  806.94   116.1  786.56
   125.8  781.22   135.5  774.95   143.5  770.23   145.2  769.23     155  767.04
   163.5  767.73   184.2  770.34   203.6  771.95   213.4   772.6   223.1  772.97
   232.8  772.99   242.6  772.74   291.2  770.26     301  770.02   310.7  770.07
   320.4  770.46   339.9  771.73   349.7  772.74   359.4  774.38   369.1  776.61
   378.9  779.43   408.1  788.85   417.8  792.71   476.2  820.76   505.4   834.6
#Mann= 3 , 0 , 0
       0      .1       0   143.5    .045       0   163.5     .06       0
#XS Ineff= 2 , 0
                          230.12          779.64
Permanent Ineff=
       F       F
Bank Sta=143.5,163.5
XS Rating Curve= 0 ,0
Exp/Cntr=0.3,0.1

Type RM Length L Ch R = 1 ,15371.8 ,230.7,234,236.9
XS GIS Cut Line= 4
     1584173.066      364676.275      1584106.66      364830.702
     1584041.035      364967.682     1584028.014      365238.515
#Sta/Elev= 30
       0  870.36    37.4  850.94    65.4  835.65    74.7  830.37   112.1  808.51
   130.7  797.28   158.8  780.62   168.1  774.01   177.6  767.74   183.8  765.61
   187.1  764.48   196.6  763.84   203.8  764.31   225.1  766.42   253.5  768.12
   291.5  769.86     320  770.59   339.4  771.38     349  771.93   358.7  772.68
   368.4  773.71   397.5  777.32   436.2  781.93   455.6  784.51   465.2  786.34
   474.9  789.48   484.6  793.61   542.7  819.35   581.4  836.26   591.1  840.34
#Mann= 3 , 0 , 0
       0      .1       0   183.8    .045       0   203.8     .06       0
Bank Sta=183.8,203.8
XS Rating Curve= 0 ,0
Exp/Cntr=0.3,0.1

Type RM Length L Ch R = 1 ,15137.8 ,195.2,195.3,194.9
XS GIS Cut Line= 3
     1583991.391      364592.209     1583763.186      364937.452
     1583590.861      365051.041
#Sta/Elev= 30
       0  871.81     9.6  868.35    28.9  859.32      77  834.03   105.9  819.47
   115.5   814.1   134.7  801.49     154  787.33   173.2  770.02   182.9  763.42
   187.4  762.37   192.5  761.18   204.4  761.23   221.4  761.85     231   763.9
   240.6  767.75   250.2  770.33   269.5   770.6   317.6  768.64   365.7  770.71
   413.8  771.86   492.5  780.97   502.3  782.72   512.1  786.48   531.8  797.42
   541.6   803.4   590.8  837.73   600.6  843.97   610.4  848.63   620.2  851.19
#Mann= 3 , 0 , 0
       0      .1       0   187.4    .045       0   204.4     .06       0
Bank Sta=187.4,204.4
XS Rating Curve= 0 ,0
Exp/Cntr=0.3,0.1

Type RM Length L Ch R = 1 ,14942.5 ,339.4,340.3,340.5
XS GIS Cut Line= 4
     1583804.924      364482.378     1583746.764      364609.114
     1583580.098      364866.058     1583486.348      364971.093
#Sta/Elev= 30
       0  850.66    37.2  832.07    74.4  810.86    83.7  804.94   120.8  778.94
   130.2  772.84   139.4  767.57     149  763.64   158.6  760.91   168.2  759.01
   177.7  758.67   180.5 758.839   244.7  765.42   273.4  767.32   302.2  768.08
     350  766.15   369.1  765.91   397.8  767.52   407.4  768.81     417  770.82
   445.7  778.25   455.1  781.05   464.5  784.91   492.6  798.43     502  803.59
   539.6   827.1   558.3   837.7   567.7  841.91   577.1  845.23   586.5  847.73
#Mann= 3 , 0 , 0
       0      .1       0   158.6    .045       0   180.5     .06       0
Bank Sta=158.6,180.5
XS Rating Curve= 0 ,0
Exp/Cntr=0.3,0.1

Type RM Length L Ch R = 1 ,14602.2 ,181.6,176.5,171.4
XS GIS Cut Line= 3
     1583612.037      364211.524     1583343.925      364610.662
     1583259.638      364769.515
#Sta/Elev= 30
       0  919.04    58.9  894.85    68.7  890.36    78.5  885.24   137.4   851.4
   186.4   822.1     265  774.08   274.8  767.49   284.6  760.12   292.6  756.39
   294.4  755.55   304.2  754.52   309.4 755.145   343.4  760.47   372.9  763.63
   392.5  764.64   402.3  764.79   451.4  763.77     471  763.97   480.8  764.39
   499.8  766.22   509.2  767.62   518.7  769.51   528.2  771.74   537.6  774.42
   547.1  777.84   575.5     790   594.4  798.67   603.9  803.77   660.7  837.37
#Mann= 3 , 0 , 0
       0      .1       0   292.6    .045       0   309.4     .06       0
Bank Sta=292.6,309.4
XS Rating Curve= 0 ,0
Exp/Cntr=0.3,0.1

Type RM Length L Ch R = 1 ,14425.6 ,160.6,165.1,169.5
XS GIS Cut Line= 3
     1583351.999      364209.793      1583181.86      364656.321
      1583181.86      364717.432
#Sta/Elev= 30
       0  868.09    48.8  838.06     117  795.78   146.3  777.86     156   771.5
   165.8  764.27   175.5  757.81   180.5  756.18   185.3  754.62     195  754.68
   196.5  754.86   214.5  756.99   224.3  757.97   243.8  759.74   253.6  760.46
     273  761.58   321.8  763.93   331.6  764.55   341.3  765.37   370.6  768.46
   409.6  772.85   419.3  774.07   429.1  776.13   438.8  779.49   468.1  792.15
   477.8  796.01   486.6   799.2     504  805.01   512.8  808.42     539  819.66
#Mann= 3 , 0 , 0
       0      .1       0   180.5    .045       0   196.5     .06       0
Bank Sta=180.5,196.5
XS Rating Curve= 0 ,0
Exp/Cntr=0.3,0.1

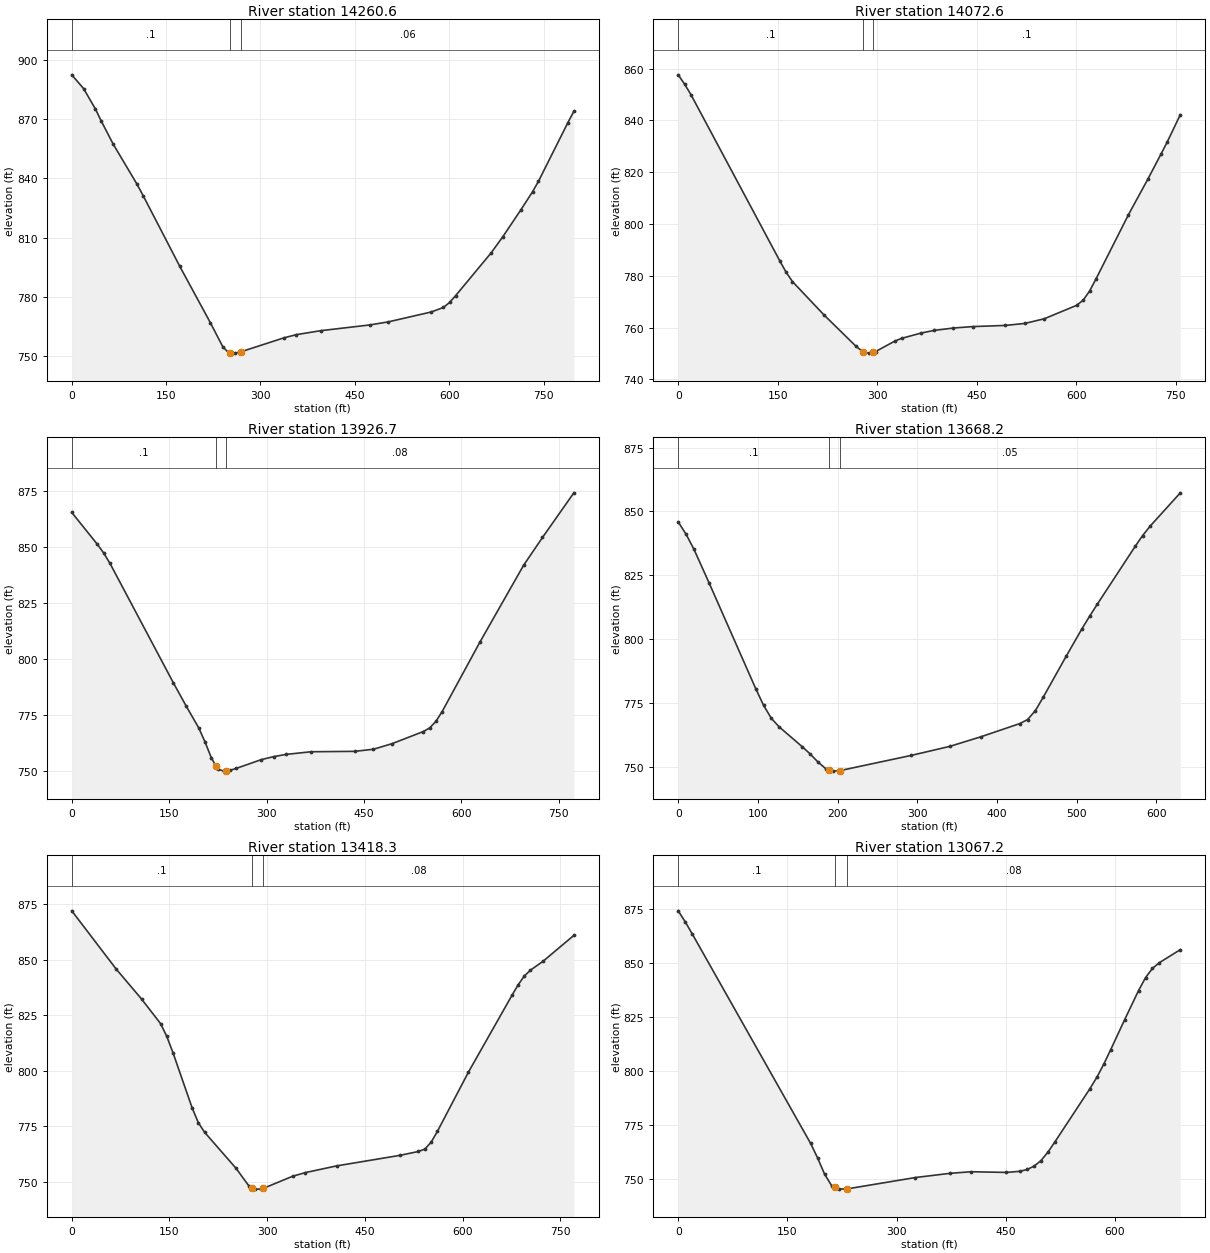
Type RM Length L Ch R = 1 ,14260.6 ,189.6,188,186.5
XS GIS Cut Line= 4
      1583304.23      364133.853      1583221.75      364178.656
     1582947.125      364615.955      1582816.73      364751.214
#Sta/Elev= 30
       0  892.44    18.8  885.48    37.5   875.2    46.9  869.03    65.7  857.44
   103.6  837.14   113.4  831.32   171.8  795.43   220.5  766.84     240  754.84
   249.8   751.6   251.3 751.594   259.5  751.56   268.9 752.249   337.4  759.31
   356.9  760.91   395.9  762.93   473.8  765.83   503.1  767.38   571.3  772.38
   590.8  774.68   600.5  777.19   610.2  780.67   666.6   802.3   685.4  810.59
   713.6  823.97   732.4  833.22   741.8  838.52   788.7   868.3   798.1  873.97
#Mann= 3 , 0 , 0
       0      .1       0   251.3    .045       0   268.9     .06       0
Bank Sta=251.3,268.9
XS Rating Curve= 0 ,0
Exp/Cntr=0.3,0.1

Type RM Length L Ch R = 1 ,14072.6 ,143.8,145.9,147.8
XS GIS Cut Line= 3
     1582949.844       363946.25     1582988.906      364191.909
     1582748.455      364639.826
#Sta/Elev= 30
       0   857.6     9.6     854    19.1  849.98   153.1  785.77   162.6   781.4
   172.2  777.76     220  764.82   268.3   752.7   278.5  750.63   287.8  750.12
   293.5  750.47   297.6  750.73     327  754.82   336.7  755.81   366.1  757.87
   385.6  758.88     415  759.82   444.3  760.37   493.2  760.82   522.5  761.58
   551.8  763.38   600.7  768.57   610.5  770.54   620.2  774.04     630   778.8
   678.9  803.58   708.2  817.34   727.8  826.91   737.6  831.79   757.1  842.21
#Mann= 3 , 0 , 0
       0      .1       0   278.5    .045       0   293.5      .1       0
Bank Sta=278.5,293.5
XS Rating Curve= 0 ,0
Exp/Cntr=0.3,0.1

Type RM Length L Ch R = 1 ,13926.7 ,265.2,258.4,249.4
XS GIS Cut Line= 4
     1582882.355      363923.089     1582867.232      364118.093
     1582650.782       364447.24     1582571.157      364612.673
#Sta/Elev= 30
       0  865.27    39.1  851.17    48.9  847.29    58.7  842.63   156.5  789.27
     176  779.02   195.6  769.15   205.2  762.94   214.8  755.94   222.1 752.086
   224.4  750.87     234  749.92   237.6 750.051   243.6  750.27   253.2  751.13
   291.7  755.04   310.9  756.39   330.1  757.38   368.5  758.56   435.8  758.74
   464.6  759.68   493.4  762.19   541.5  767.59   551.1  769.19   560.7  772.11
   570.3  776.48   628.2  807.32   695.8  841.75   724.8  854.11   773.1  874.02
#Mann= 3 , 0 , 0
       0      .1       0   222.1    .045       0   237.6     .08       0
Bank Sta=222.1,237.6
XS Rating Curve= 0 ,0
Exp/Cntr=0.3,0.1

Type RM Length L Ch R = 1 ,13668.2 ,251.1,250,248.2
XS GIS Cut Line= 3
     1582658.049      363932.326     1582532.305      364443.161
     1582486.348      364536.492
#Sta/Elev= 30
       0  845.91     9.7  841.17    19.5  835.37      39  821.86    97.4  780.58
   107.2  774.09   116.9  769.04   126.6  765.74   155.9  757.88   165.6  755.11
   175.4  751.96   185.1  749.37     189  748.98   194.8   748.4   203.2 748.623
   292.3  754.54     341   758.1     380  761.86   428.7  767.01   438.4  768.57
   448.2  772.07   457.9  777.24   487.1  793.49   506.6  804.08   516.3  809.03
   526.1  813.81   573.4  836.33   582.8  840.58   592.3  844.29   630.1   857.3
#Mann= 3 , 0 , 0
       0      .1       0     189    .045       0   203.2     .05       0
Bank Sta=189,203.2
XS Rating Curve= 0 ,0
Exp/Cntr=0.3,0.1

Type RM Length L Ch R = 1 ,13418.3 ,358.7,351.1,343
XS GIS Cut Line= 4
     1582515.341      363819.392     1582404.924      363899.253
     1582327.331      364326.962     1582349.976      364525.555
#Sta/Elev= 30
       0  872.08    68.1  845.86   107.1  832.33   136.3  821.25   145.9  815.46
   155.6  807.94   184.6   783.4   194.2  776.64   203.9  772.26   252.2     756
   271.5  748.24   277.2 747.289   281.2  746.62   290.8  746.63   293.9  746.94
   339.1  752.43   358.4  754.06   406.7   757.1   503.3  761.82   532.3   763.6
     542  764.67   551.6  767.73   561.3  772.64     609  799.38   675.7  833.94
   685.2  838.66   694.7  842.67   704.2  845.34   723.2  849.26   770.8  861.01
#Mann= 3 , 0 , 0
       0      .1       0   277.2    .045       0   293.9     .08       0
Bank Sta=277.2,293.9
XS Rating Curve= 0 ,0
Exp/Cntr=0.3,0.1

Type RM Length L Ch R = 1 ,13067.2 ,205.4,201.5,196.7
XS GIS Cut Line= 4
     1581989.125      363764.661     1582035.379       363950.58
     1582084.115      364234.279     1582084.698      364444.869
#Sta/Elev= 30
       0  874.17     9.6  869.06    19.2  863.49     182  766.25   191.6  759.48
   201.2  751.97   210.8   746.7   215.3 745.934   220.4  745.07   232.5 745.208
   325.9  750.45   373.9  752.41   402.7  753.14   450.7  752.82   469.8  753.35
   479.4  754.19     489   755.7   498.6  758.34   508.2  762.29   517.7     767
   565.6  791.58   575.2  796.88   584.7  802.96   594.3  809.74   613.4   823.6
   632.6  837.16   642.2  843.18   651.7  847.47   661.3  850.14     690  856.17
#Mann= 3 , 0 , 0
       0      .1       0   215.3    .045       0   232.5     .08       0
Bank Sta=215.3,232.5
XS Rating Curve= 0 ,0
Exp/Cntr=0.3,0.1

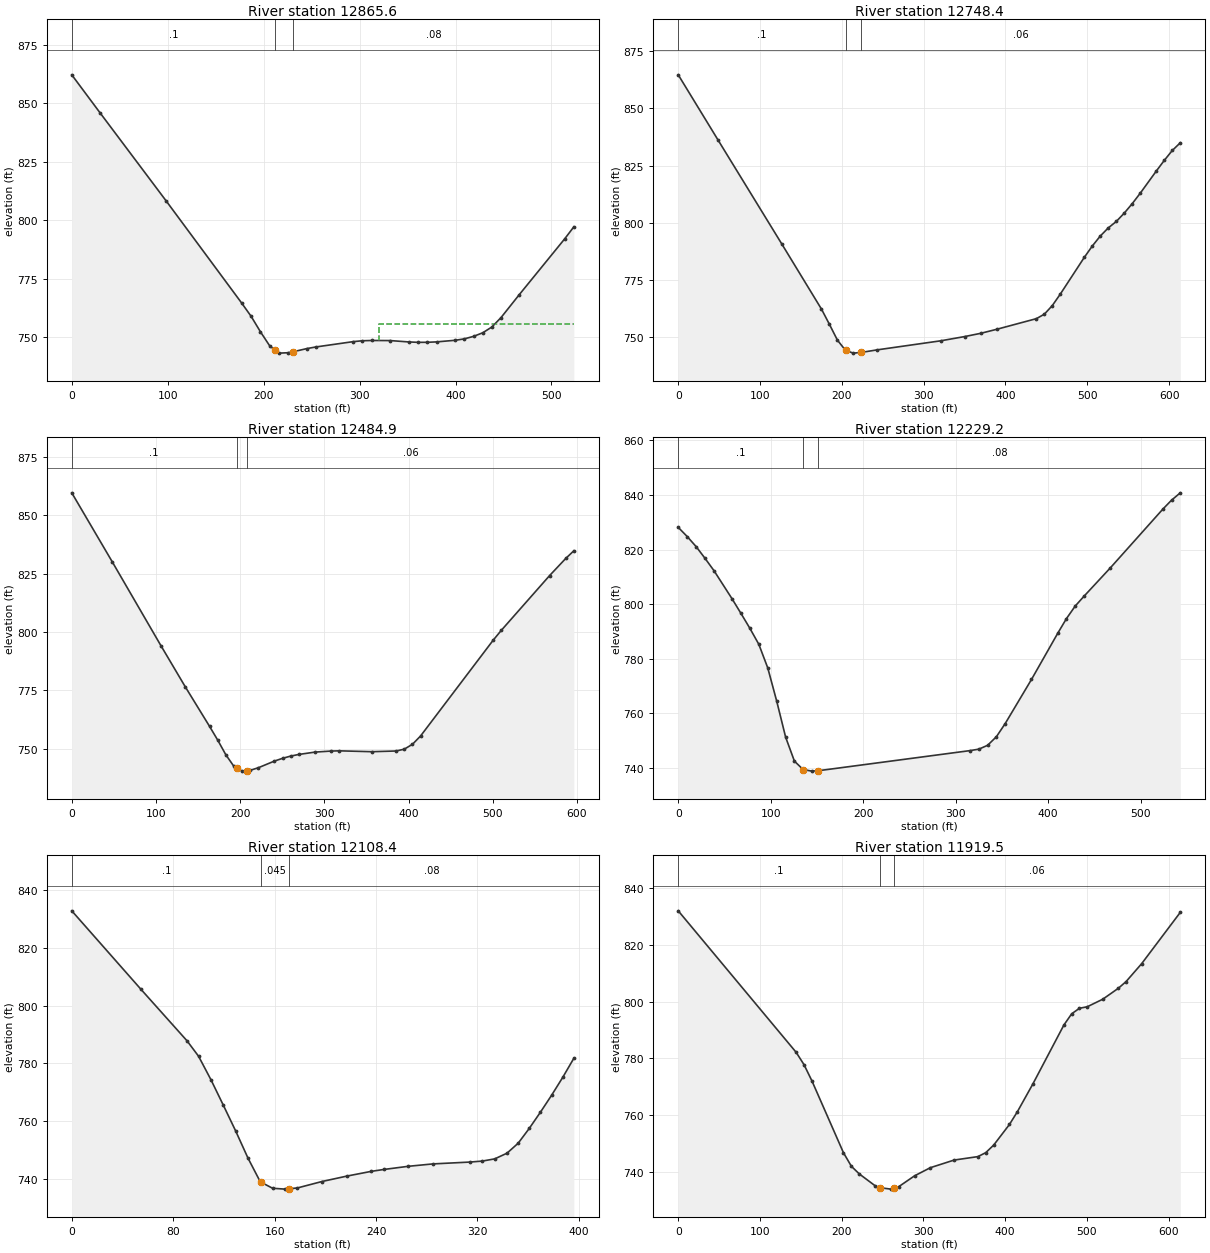
Type RM Length L Ch R = 1 ,12865.6 ,114.4,117.2,120.1
XS GIS Cut Line= 4
     1581794.352      363850.248     1581849.213      364039.137
     1581932.617       364255.35     1581948.519      364348.859
#Sta/Elev= 30
       0  862.09    29.5  845.85    98.4  808.24     177  764.69   186.9     759
   196.7  752.34   206.4   746.3     212 744.529     216  743.26   225.7  743.43
   231.1 743.874     245   745.2   254.6   745.9   293.2  748.16   302.9  748.54
   312.6  748.66   331.9  748.62   351.2  748.04   360.8  747.87   370.5  747.88
   380.2  748.06   399.5  748.74   409.1  749.34   418.8  750.42   428.4  751.96
   437.9  754.43   447.4  758.44   466.4  768.22   513.8  792.08   523.3  797.19
#Mann= 3 , 0 , 0
       0      .1       0     212    .045       0   231.1     .08       0
#XS Ineff= 2 , 0
                          319.93          755.71
Permanent Ineff=
       F       F
Bank Sta=212,231.1
XS Rating Curve= 0 ,0
Exp/Cntr=0.3,0.1

Type RM Length L Ch R = 1 ,12748.4 ,266.3,263.5,260.8
XS GIS Cut Line= 3
     1581693.076      363881.106      1581805.65       364344.31
     1581897.697      364445.759
#Sta/Elev= 30
       0  864.64    48.6   836.2   126.5  790.81   175.1  762.31   184.8  755.67
   194.6  748.75   204.5 744.295     214  743.09   223.3  743.37   243.2  744.52
     321  748.48   350.2  750.33   369.7  751.74   389.1  753.48   437.8  758.15
   447.5   760.1   457.2  763.84     467  768.86   496.3  784.89     506  789.81
   515.8   794.2   525.6  797.77   535.4  800.58   545.2  804.25     555   808.4
   564.8  812.97   584.3  822.59   594.1  827.27   603.9   831.6   613.7  834.97
#Mann= 3 , 0 , 0
       0      .1       0   204.5    .045       0   223.3     .06       0
Bank Sta=204.5,223.3
XS Rating Curve= 0 ,0
Exp/Cntr=0.3,0.1

Type RM Length L Ch R = 1 ,12484.9 ,263.1,255.6,248.1
XS GIS Cut Line= 4
     1581440.663      363969.448     1581478.126      364128.837
     1581563.255      364354.233     1581605.246      364541.323
#Sta/Elev= 30
       0  859.63    48.2  829.99   105.9  794.12   134.8   776.5   163.7  759.51
   173.4  753.61     183  747.36   192.6  742.38   195.7 741.728   202.3  740.34
   208.4 740.562   211.9  740.69   221.6  741.79   240.8  744.66   250.5  745.84
   260.1  746.79   269.7  747.49     289   748.5   308.3  748.95   317.9  749.04
   356.5  748.67   385.4  748.97     395  749.76   404.7  751.85   414.3  755.39
   500.5  796.43   510.1  800.63   567.6  824.16   586.8  831.51   596.4  834.79
#Mann= 3 , 0 , 0
       0      .1       0   195.7    .045       0   208.4     .06       0
Bank Sta=195.7,208.4
XS Rating Curve= 0 ,0
Exp/Cntr=0.3,0.1

Type RM Length L Ch R = 1 ,12229.2 ,125.5,120.8,116.1
XS GIS Cut Line= 4
     1581162.671      364178.354     1581248.609      364256.479
     1581400.592      364438.757     1581481.617      364609.865
#Sta/Elev= 30
       0  828.12     9.7  824.76    19.4  821.05      29  816.76    38.7  812.23
    58.1     802    67.8  796.61    77.4  791.16    87.1  785.29    96.8  776.61
   106.5  764.39   116.1  751.26   125.6  742.46   135.1  739.36   144.6   738.8
   151.5  738.95   315.5  746.32     325  746.85   334.5  748.27     344  751.42
   353.5  756.24   381.9  772.39   410.3  789.33   419.7  794.69   429.2   799.3
   438.7  802.89   467.1  813.26   523.9   834.8   533.3  838.08   542.8  840.78
#Mann= 3 , 0 , 0
       0      .1       0   135.1    .045       0   151.5     .08       0
Bank Sta=135.1,151.5
XS Rating Curve= 0 ,0
Exp/Cntr=0.3,0.1

Type RM Length L Ch R = 1 ,12108.4 ,191.4,188.9,186.2
XS GIS Cut Line= 4
     1581073.519      364253.026     1581138.102      364329.415
     1581329.074      364480.109     1581363.797      364519.693
#Sta/Elev= 30
       0  832.77    54.6  805.62    90.9  787.83     100   782.5   109.8  774.35
   119.5   765.6   129.2  756.73     139  747.26   148.7  739.07   149.5 738.886
   158.4  736.85   168.2  736.55   171.6 736.693   177.9  736.95   197.3  739.18
   216.8  741.04   236.3   742.7     246  743.34   265.4  744.44   284.9  745.27
   314.1  745.91   323.8  746.25   333.6  747.01   343.3  748.98   352.1  752.43
   360.8  757.52   369.6  763.12   378.4  768.97   387.2  775.16     396  781.79
#Mann= 3 , 0 , 0
       0      .1       0   149.5    .045       0   171.6     .08       0
Bank Sta=149.5,171.6
XS Rating Curve= 0 ,0
Exp/Cntr=0.3,0.1

Type RM Length L Ch R = 1 ,11919.5 ,198.3,210.4,222.1
XS GIS Cut Line= 4
     1580931.235      364341.028     1581003.645      364476.825
     1581226.172      364613.435     1581409.273       364692.46
#Sta/Elev= 30
       0  831.87   144.3  782.17   153.9  777.84   163.6  772.13   202.2  746.89
   211.9  742.13   221.6  739.44   240.9   735.3     247   734.6   260.3  734.11
   263.5 734.406     270  735.01   289.3   738.8   308.6  741.65   337.6  744.32
   366.7  745.53   376.3  746.92     386  749.57   405.3  756.82     415  761.29
     434  771.07     472  791.79   481.5  795.71     491  797.64   500.5  798.17
   519.5  800.82   538.5  804.65     548  807.01     567  813.27   614.4  831.34
#Mann= 3 , 0 , 0
       0      .1       0     247    .045       0   263.5     .06       0
Bank Sta=247,263.5
XS Rating Curve= 0 ,0
Exp/Cntr=0.3,0.1

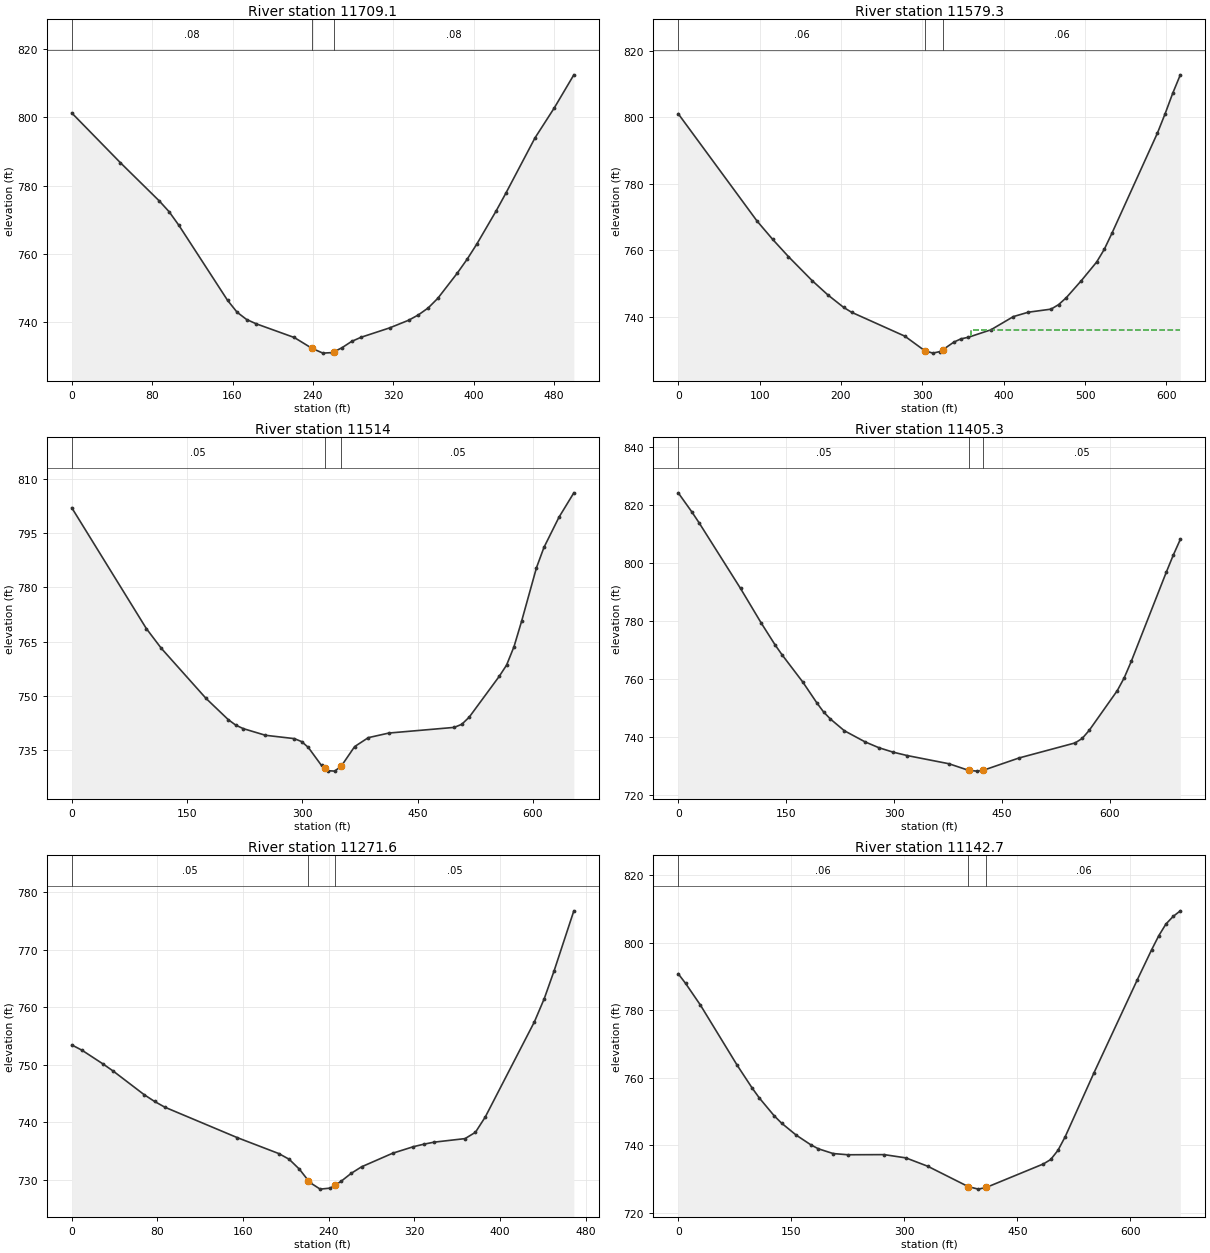
Type RM Length L Ch R = 1 ,11709.1 ,130.6,129.8,128.9
XS GIS Cut Line= 4
     1580891.955      364451.314     1580918.344      364604.092
     1581004.455      364762.425     1581127.372      364871.453
#Sta/Elev= 30
       0  801.24    48.4  786.69    87.2  775.48    96.9  772.35   106.6  768.38
     155  746.46   164.5  742.97     174  740.84   183.5  739.59   221.4  735.58
     239 732.415   249.9  731.01   259.4  731.17     261  731.41   268.9  732.59
   278.4  734.42   287.8  735.64   316.3  738.39   335.3  740.64   344.9  742.19
   354.6  744.21   364.3  747.06   383.6   754.4   393.3  758.42   402.9  762.83
   422.3   772.6   431.9  777.75   460.9  793.93   480.2  802.75   499.6  812.39
#Mann= 3 , 0 , 0
       0     .08       0     239    .045       0     261     .08       0
Bank Sta=239,261
XS Rating Curve= 0 ,0
Exp/Cntr=0.3,0.1

Type RM Length L Ch R = 1 ,11579.3 ,65.3,65.3,65.3
XS GIS Cut Line= 6
     1580800.983      364448.537      1580810.09      364671.023
     1580833.708      364721.639     1580868.934      364780.883
     1580905.528       364865.34     1581064.872      364943.675
#Sta/Elev= 30
       0  801.07    96.8  768.84   116.2  763.28   135.5  758.12   164.6  750.91
     184   746.6   203.3  742.87     213  741.41   278.5  734.22   303.1  729.83
     313  729.12   321.6  729.59   325.1 730.119   338.8  732.44   347.4   733.4
   356.7   733.9   384.3  736.13   411.9   740.1   430.3  741.42   458.2  742.34
   467.5   743.7   476.9  745.77   495.6  750.95   514.3  756.51   523.6   760.3
     533  765.12     589  795.28   598.4  801.06   607.7  807.19   617.1  812.77
#Mann= 3 , 0 , 0
       0     .06       0   303.1    .045       0   325.1     .06       0
#XS Ineff= 2 , 0
       0                     360       0     736
Permanent Ineff=
       F       F
Bank Sta=303.1,325.1
XS Rating Curve= 0 ,0
Exp/Cntr=0.3,0.1

Type RM Length L Ch R = 1 ,11514   ,102.6,108.7,114.4
XS GIS Cut Line= 6
       1580748.9      364453.137     1580749.049      364695.689
     1580772.944        364746.9      1580808.17      364806.144
     1580836.516      364871.565     1580817.476      365084.648
#Sta/Elev= 30
       0  802.13      97   768.6   116.4  763.14   174.6  749.23   203.7   743.3
   213.4  741.79   223.2  740.82     252  738.98   289.6  738.05   299.1  737.22
   307.7  735.62   324.9   730.6   329.2  729.88   333.5  729.15   342.1  729.03
   350.8  730.47     368  735.84   385.8  738.32   412.6   739.6   497.6  741.17
   507.4  742.03   517.1  744.02     556   755.3   565.7  758.46   575.4  763.61
   585.2  770.61   604.6   785.5   614.3  791.12   633.8  799.48   653.2  806.27
#Mann= 3 , 0 , 0
       0     .05       0   329.2    .045       0   350.8     .05       0
Bank Sta=329.2,350.8
XS Rating Curve= 0 ,0
Exp/Cntr=0.3,0.1

Type RM Length L Ch R = 1 ,11405.3 ,137.7,133.8,129.3
XS GIS Cut Line= 3
     1580660.295      364406.929     1580653.916      364685.833
     1580767.311      365089.188
#Sta/Elev= 30
       0  824.07    19.2   817.4    28.9  813.79    86.6  791.14   115.4  779.22
   134.7  771.68   144.3   768.3   173.2  758.89   192.4  751.84     202  748.62
   211.6  746.16   230.9  742.14   259.7   738.3     279  736.28   298.5  734.77
     318   733.6   376.4  730.76   403.6   728.5   415.4  728.22   423.6  728.47
   473.9  732.76   551.8  737.94   561.6  739.48   571.3  742.25   610.3  755.92
     620  760.36   629.8  766.01   678.5  796.73   688.2  802.61     698  808.03
#Mann= 3 , 0 , 0
       0     .05       0   403.6    .045       0   423.6     .05       0
Bank Sta=403.6,423.6
XS Rating Curve= 0 ,0
Exp/Cntr=0.3,0.1

Type RM Length L Ch R = 1 ,11271.6 ,130.3,128.9,127.7
XS GIS Cut Line= 4
     1580501.913      364617.475     1580519.621      364761.385
     1580621.704      364969.689     1580633.857      365060.835
#Sta/Elev= 30
       0  753.45     9.7  752.51      29  750.16    38.7   748.9    67.7  744.78
    77.3  743.62      87  742.61   154.7  737.31   193.3  734.55     203  733.56
   212.6  731.83     221  729.83   222.3  729.52     232  728.36   241.6  728.54
   245.7  729.03   251.3  729.69     261  731.11   270.6  732.24   299.6   734.6
     319  735.74   328.6  736.17   338.3  736.53   367.3  737.15     377  738.25
   386.2  740.92   432.1  757.48   441.3  761.52   450.5  766.36   468.9  776.78
#Mann= 3 , 0 , 0
       0     .05       0     221    .045       0   245.7     .05       0
Bank Sta=221,245.7
XS Rating Curve= 0 ,0
Exp/Cntr=0.3,0.1

Type RM Length L Ch R = 1 ,11142.7 ,154.4,154.4,154.5
XS GIS Cut Line= 4
     1580328.066      364537.396     1580370.384      364768.516
     1580500.103      364993.241     1580524.464      365163.482
#Sta/Elev= 30
       0  790.82     9.8  787.95    29.4  781.55    78.3  763.67    97.9  757.01
   107.7  753.97   127.3  748.72   137.1  746.54   156.6  742.97   176.2  740.07
     186  738.92   205.6  737.51   225.2  737.15   273.4  737.19   302.2  736.22
   331.1  733.75   385.1 727.688   398.3  726.96   409.1 727.484   484.8  734.44
   494.4  735.75     504  738.46   513.6   742.5   551.8  761.45   609.1  788.93
   628.2  797.88   637.8   802.1   647.3  805.56   656.9  807.82   666.4  809.48
#Mann= 3 , 0 , 0
       0     .06       0   385.1    .045       0   409.1     .06       0
Bank Sta=385.1,409.1
XS Rating Curve= 0 ,0
Exp/Cntr=0.3,0.1