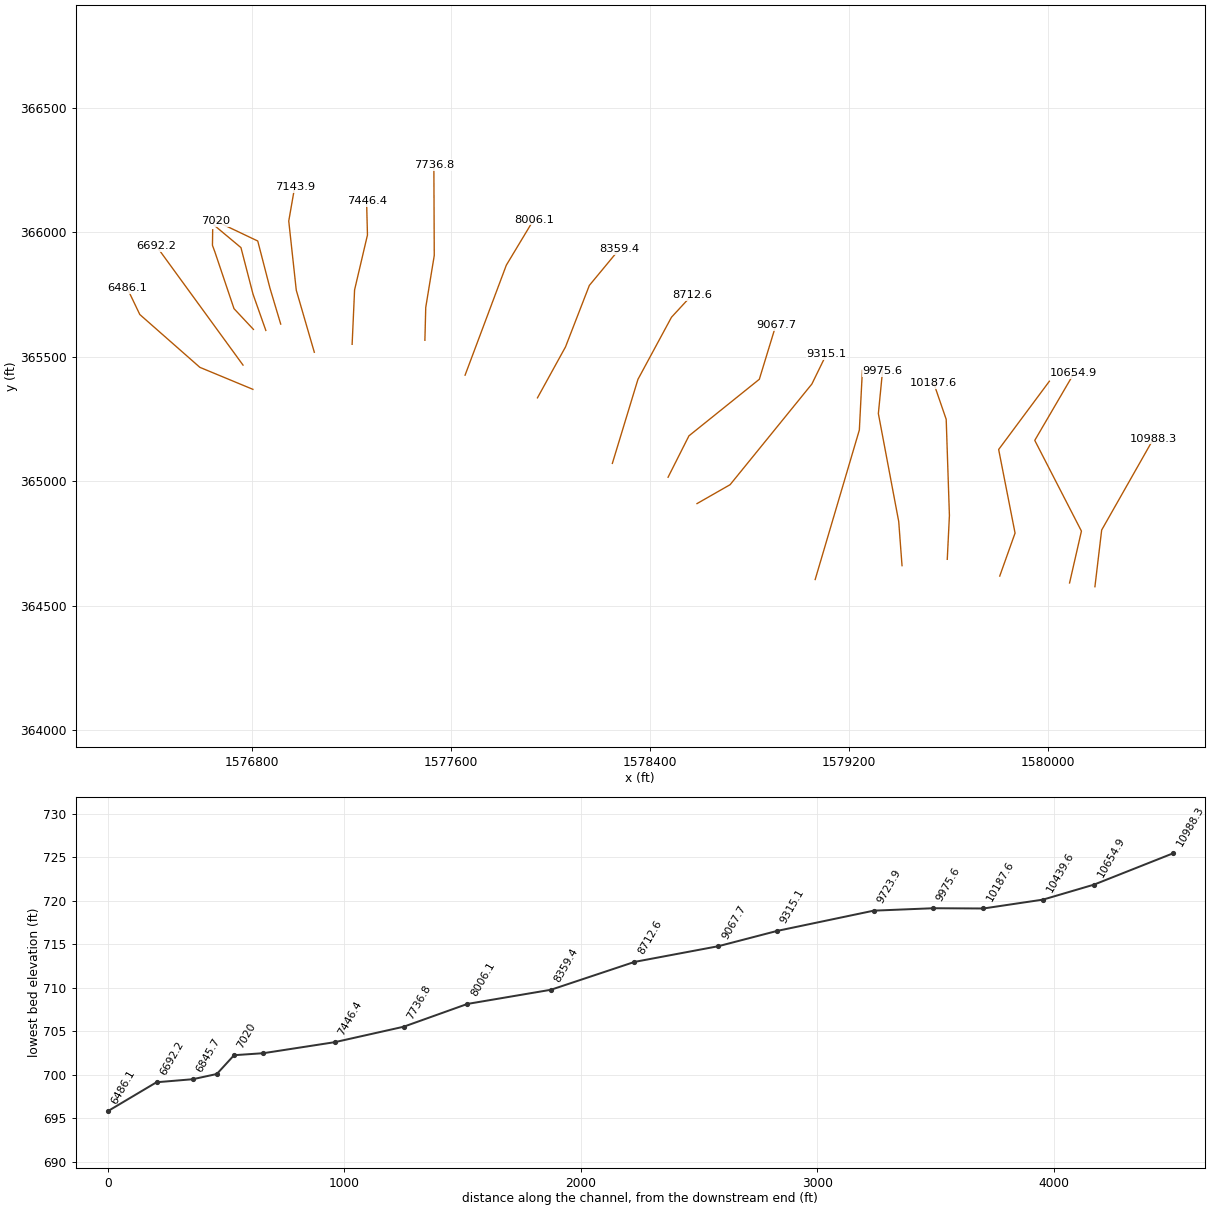
HEC-RAS study GORRLRN1.prj: GORRLRN1

--- GORRLRN1.g01 (geometry) --- (continued)

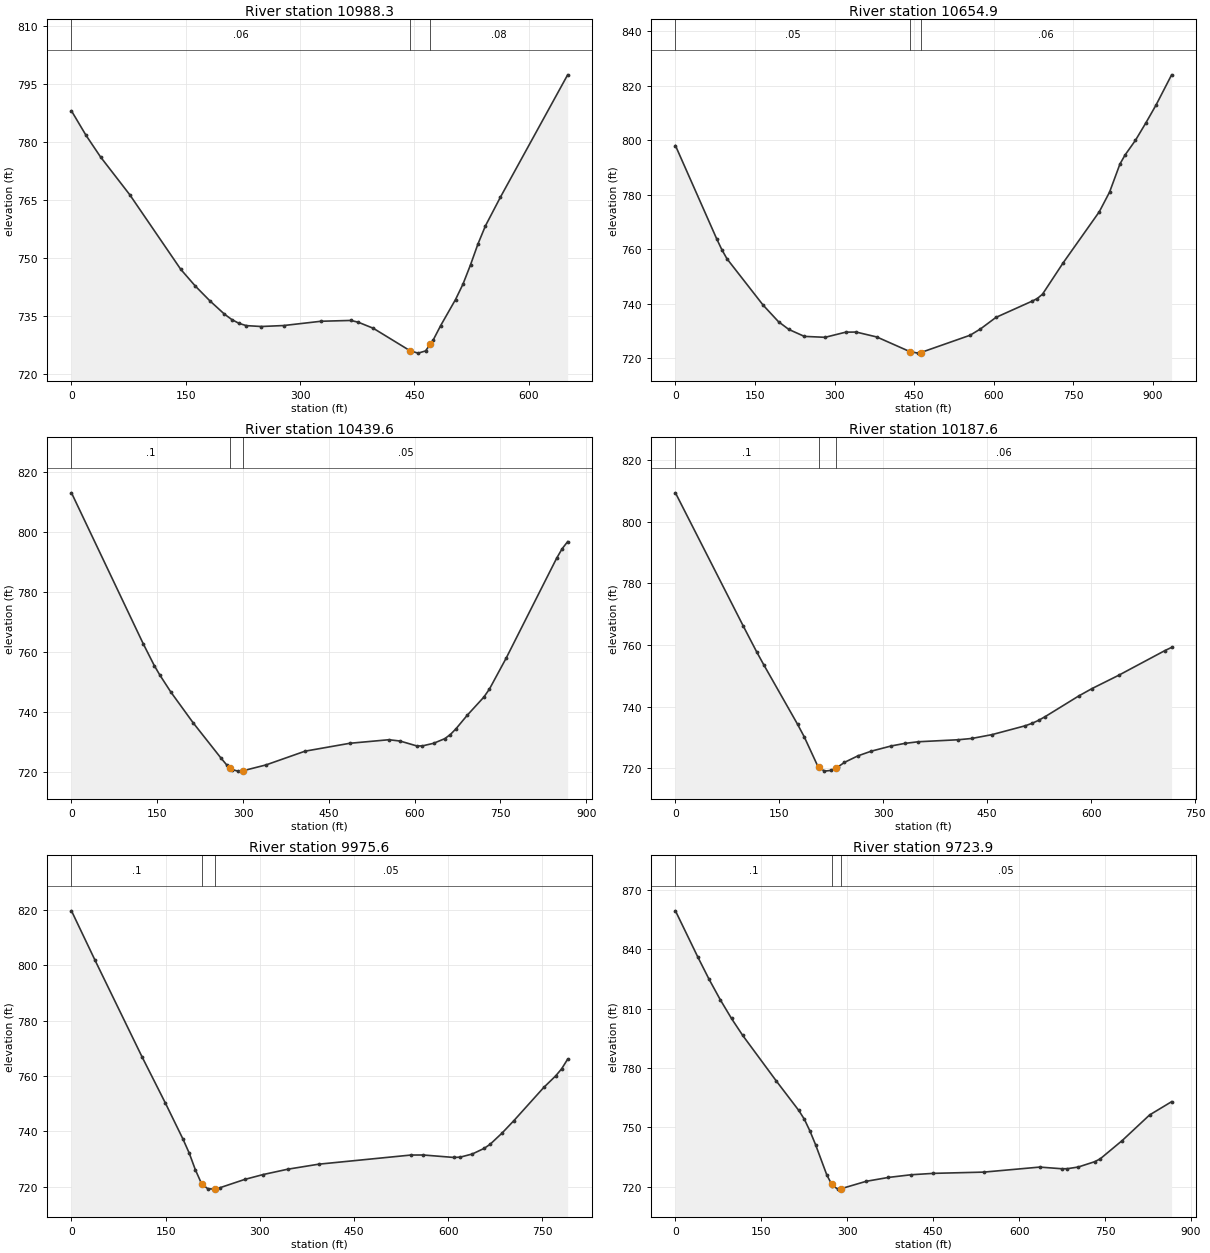
Type RM Length L Ch R = 1 ,10988.3 ,310.6,333.4,355.6
XS GIS Cut Line= 3
     1580189.177      364576.459     1580216.304      364804.324
     1580424.638      365171.077
#Sta/Elev= 30
       0  788.15    19.1  781.82    38.2  776.22    76.5  766.45   143.4  747.15
   162.5  742.82   181.7  738.98   200.8  735.54   210.4  734.15   219.9  733.15
   229.5  732.57   249.1  732.34   278.5  732.59   327.6   733.7   366.8  733.91
   376.6  733.44   396.2  731.88   444.8  726.02   455.1  725.45   464.8  726.02
   470.8 727.705   474.7   728.8   484.5  732.54   504.1  739.32   513.9  743.31
   523.8  748.31   533.6  753.72   543.4   758.4     563   765.8   651.3  797.48
#Mann= 3 , 0 , 0
       0     .06       0   444.8    .045       0   470.8     .08       0
Bank Sta=444.8,470.8
XS Rating Curve= 0 ,0
Exp/Cntr=0.3,0.1

Type RM Length L Ch R = 1 ,10654.9 ,222.2,215.3,207.9
XS GIS Cut Line= 4
     1580087.181       364591.65     1580134.924      364799.983
     1579947.207      365164.567     1580104.512      365433.495
#Sta/Elev= 30
       0  797.99    77.7  763.81    87.4  759.83    97.2  756.45   165.2  739.49
   194.3  733.38   213.7  730.56     243     728   282.1  727.66   321.1  729.55
   340.7  729.59   379.7  727.78   442.6  722.36   457.8  721.86     462 722.037
   555.5  728.42     575  730.72   604.3  734.97   672.5  740.93   682.2  741.89
     692  743.47   730.9  754.96   799.1  773.72   818.5  780.94     838  791.22
   847.7  794.54   867.2   799.9   886.7  806.24   906.2   812.9   935.4  823.92
#Mann= 3 , 0 , 0
       0     .05       0   442.6    .045       0     462     .06       0
Bank Sta=442.6,462
XS Rating Curve= 0 ,0
Exp/Cntr=0.3,0.1

Type RM Length L Ch R = 1 ,10439.6 ,254.8,252,248.8
XS GIS Cut Line= 4
     1579806.335      364619.258     1579867.967      364792.002
     1579801.994      365127.939     1580005.987      365402.245
#Sta/Elev= 30
       0   813.2   125.5  762.72   144.8  755.44   154.4   752.3   173.8  746.57
   212.8  736.29   261.7  724.44   271.4  722.22     278 721.162   281.2  720.65
     291  720.14   300.2  720.28   339.9   722.2   408.4  726.81   486.6  729.45
   555.1  730.64   574.6   730.2   603.9  728.56   613.7  728.58   633.2  729.45
   652.7  730.99   662.5  732.38   672.3  734.29   691.8  738.78   721.1   744.9
   730.9  747.61   760.2  757.97   848.1  791.24   857.8  794.47   867.6  796.88
#Mann= 3 , 0 , 0
       0      .1       0     278    .045       0   300.2     .05       0
Bank Sta=278,300.2
XS Rating Curve= 0 ,0
Exp/Cntr=0.3,0.1

Type RM Length L Ch R = 1 ,10187.6 ,208.5,212,215.4
XS GIS Cut Line= 4
     1579595.315      364686.616     1579603.966      364862.651
     1579591.013      365249.116     1579541.149      365393.908
#Sta/Elev= 30
       0  809.37    97.9  766.17   117.5  757.69   127.3  753.68   176.2  734.34
   185.9  730.24   205.2  720.85     207 720.529   214.9  719.12   224.6  719.36
     232 720.185   234.2  720.43   243.9  721.95   263.2  724.06   282.6  725.59
   311.6  727.29   330.9  728.11   350.2  728.64   408.3   729.3   427.6  729.71
   456.6  730.94   504.9  733.83   514.6  734.62   524.3  735.61   533.9  736.83
   582.1   743.5   601.2  745.89   639.5  750.18   706.5  758.22   716.1  759.25
#Mann= 3 , 0 , 0
       0      .1       0     207    .045       0     232     .06       0
Bank Sta=207,232
XS Rating Curve= 0 ,0
Exp/Cntr=0.3,0.1

Type RM Length L Ch R = 1 ,9975.6  ,262.3,251.7,240.9
XS GIS Cut Line= 4
     1579413.348      364661.156     1579400.077      364838.356
     1579318.178      365272.261     1579334.876      365442.406
#Sta/Elev= 30
       0  819.71    37.4  801.91   112.2  767.03   149.6  750.23   177.7  737.17
   187.5  732.18   197.3  726.14   207.1  721.15   208.5 720.888     217   719.3
   226.8  719.15   228.5  719.24   236.6  719.67   275.8  722.65   305.3  724.42
   344.5  726.35   393.6  728.16   540.8  731.47   560.4  731.48   609.4  730.59
   619.3  730.72   638.3  731.84   657.2  733.87   666.8  735.37   685.8  739.42
   704.7  743.93   752.2   755.9   771.2  760.09   780.7  762.65   790.2  766.11
#Mann= 3 , 0 , 0
       0      .1       0   208.5    .045       0   228.5     .05       0
Bank Sta=208.5,228.5
XS Rating Curve= 0 ,0
Exp/Cntr=0.3,0.1

Type RM Length L Ch R = 1 ,9723.9  ,417.5,408.7,399.7
XS GIS Cut Line= 3
     1579064.065      364605.453     1579241.706      365206.273
     1579253.938      365445.731
#Sta/Elev= 30
       0  859.38    39.2  835.99    58.7  824.84    78.3  814.49    97.9  805.02
   117.5  796.46   176.2  773.44   215.4  758.58   225.2   754.1     235  748.11
   244.7  741.29   264.3  726.03   272.8  721.33   274.1  720.61   283.9  718.87
   288.8 719.046   332.8   722.8     372  724.78   411.2  726.12   450.3  726.83
   538.4  727.46   636.1     730   674.5  729.16   684.1  729.18   703.3  730.03
     732  732.72   741.6  734.15     780  743.39   827.9  756.33   866.3  763.02
#Mann= 3 , 0 , 0
       0      .1       0   272.8    .045       0   288.8     .05       0
Bank Sta=272.8,288.8
XS Rating Curve= 0 ,0
Exp/Cntr=0.3,0.1

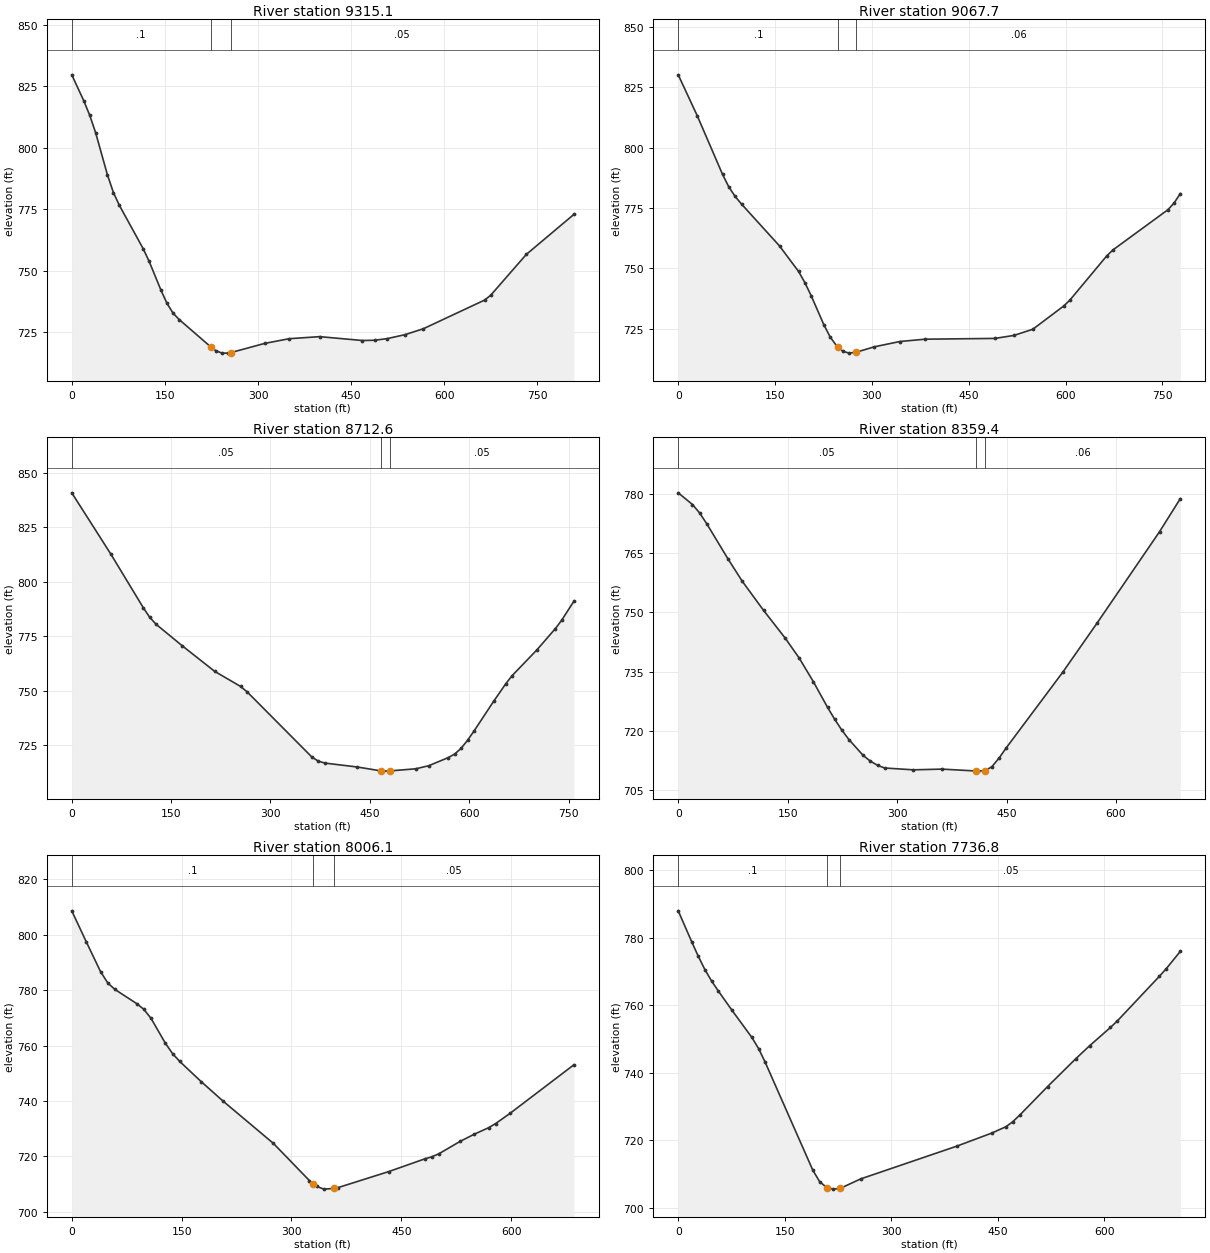
Type RM Length L Ch R = 1 ,9315.1  ,252,247.4,242.7
XS GIS Cut Line= 4
     1578588.738      364910.505     1578721.943      364986.554
     1579050.731      365390.998     1579109.659      365511.373
#Sta/Elev= 30
       0  829.67    19.2  819.21    28.8   813.3    38.4  806.17    57.5  788.96
    67.1   781.8    76.7  776.59     115     759   124.6  753.85   143.8  742.05
   153.4  736.75   163.2  732.77     173  730.19   223.7 719.115   232.1  717.52
   241.9  716.55   251.7  716.54   255.7  716.72   310.7  720.49   350.1   722.4
   399.2  723.24   468.1  721.67   487.8  721.77   507.4  722.41   536.9  724.06
   566.4  726.47   664.8   738.1   674.6  740.04     732  756.66   808.6  772.92
#Mann= 3 , 0 , 0
       0      .1       0   223.7    .045       0   255.7     .05       0
Bank Sta=223.7,255.7
XS Rating Curve= 0 ,0
Exp/Cntr=0.3,0.1

Type RM Length L Ch R = 1 ,9067.7  ,346.2,355.1,364.2
XS GIS Cut Line= 4
     1578472.419      365016.494     1578556.341       365182.81
      1578839.42      365410.123     1578906.273      365628.474
#Sta/Elev= 30
       0   830.2    29.4  813.26    68.6  788.94    78.4  783.68    88.2  779.75
      98  776.61   156.9  759.23   186.3   748.7   196.1  744.06   205.9  738.62
   225.5   726.6   235.4  721.46   245.2  717.85   248.1 717.172     255  715.56
   264.8  714.79   276.1  715.21     304  717.42   343.3  719.61   382.5  720.57
   490.5  720.89   519.9  722.13   549.3   724.7   596.9   734.3   606.4   736.7
   663.5  755.04     673  757.52   758.7   774.3   768.2  777.11   777.7  780.96
#Mann= 3 , 0 , 0
       0      .1       0   248.1    .045       0   276.1     .06       0
Bank Sta=248.1,276.1
XS Rating Curve= 0 ,0
Exp/Cntr=0.3,0.1

Type RM Length L Ch R = 1 ,8712.6  ,350.2,353.2,355.5
XS GIS Cut Line= 4
     1578248.305      365072.109     1578351.157      365409.625
     1578486.167      365659.469     1578568.444      365748.497
#Sta/Elev= 30
       0  840.89    58.8  812.81   107.8  788.18   117.6   783.7   127.4  780.45
   166.6  770.64   215.6  758.87   254.8  751.91   264.6  749.46   362.6  719.43
   372.4  717.54   382.2  716.68   431.2  714.87   466.2 713.125   470.4  712.98
   480.1  713.08   519.3  714.05   538.9  715.46   568.3  719.19   578.1  720.82
   587.9   723.5   597.7  727.24   607.4  731.46   636.8  745.02   655.5  753.25
   664.8  756.87   702.1  768.67   730.1  778.49   739.4  782.22     758  791.04
#Mann= 3 , 0 , 0
       0     .05       0   466.2    .045       0   480.1     .05       0
Bank Sta=466.2,480.1
XS Rating Curve= 0 ,0
Exp/Cntr=0.3,0.1

Type RM Length L Ch R = 1 ,8359.4  ,353.1,353.3,351.8
XS GIS Cut Line= 4
     1577947.148      365335.535     1578059.995      365540.396
     1578155.784      365787.288     1578276.662      365933.104
#Sta/Elev= 30
       0  780.29    19.5  777.33    29.2  775.22      39  772.48    68.2  763.55
    87.7   757.9   116.9  750.52   146.2  743.57   165.7  738.45   185.2  732.44
   204.6  725.95   214.4  722.92   224.1   720.2   233.9  717.78   253.5  713.75
   263.3  712.31   273.1  711.26   282.9  710.57   322.2  710.11   361.4  710.29
   407.7  709.82   410.4  709.78   420.7 709.895     430  710.93   439.9  713.14
   449.7  715.72   527.1  734.87   574.5  747.42   659.7  770.46   688.1  778.82
#Mann= 3 , 0 , 0
       0     .05       0   407.7    .045       0   420.7     .06       0
Bank Sta=407.7,420.7
XS Rating Curve= 0 ,0
Exp/Cntr=0.3,0.1

Type RM Length L Ch R = 1 ,8006.1  ,264.5,269.4,275.4
XS GIS Cut Line= 3
     1577655.954      365426.532     1577821.772      365868.495
     1577931.928      366051.362
#Sta/Elev= 30
       0  808.63    19.7   797.5    39.3  786.68    49.2  782.57      59  780.23
    88.5  775.16    98.3   773.1   108.2  769.82   127.8  760.82   137.7  757.06
   147.5  754.23     177  746.89   206.5  739.95   275.4  724.64   324.5  711.22
     330 710.065   334.4  709.14   344.2  708.15   357.4  708.39   363.9  708.73
   432.7  714.48   481.8  719.06   491.4   719.8   501.2  720.91   530.3   725.4
   549.7     728   569.1  730.32   578.8  731.84   598.2  735.47   685.5  753.03
#Mann= 3 , 0 , 0
       0      .1       0     330    .045       0   357.4     .05       0
Bank Sta=330,357.4
XS Rating Curve= 0 ,0
Exp/Cntr=0.3,0.1

Type RM Length L Ch R = 1 ,7736.8  ,291.7,290.3,289
XS GIS Cut Line= 4
     1577494.352      365566.915     1577497.795      365698.905
     1577532.002      365907.366     1577530.439      366271.257
#Sta/Elev= 30
       0   787.9    18.9  778.78    28.3  774.42    37.7  770.44    47.2  767.06
    56.6  764.13    75.4  758.55   103.7  750.43   113.2  747.13   122.6  743.03
   189.6  711.12   199.2  707.74   208.8  706.05   210.1  705.98   218.5  705.53
   228.5 705.785   256.9  708.55   392.5  718.26   441.6  722.12   461.3  723.97
   471.1  725.46     481  727.43   520.3   735.9   559.6  744.05   579.3  747.94
   608.8  753.38   618.7  755.36   677.7  768.52   687.5   770.8   707.2  775.91
#Mann= 3 , 0 , 0
       0      .1       0   210.1    .045       0   228.5     .05       0
Bank Sta=210.1,228.5
XS Rating Curve= 0 ,0
Exp/Cntr=0.3,0.1

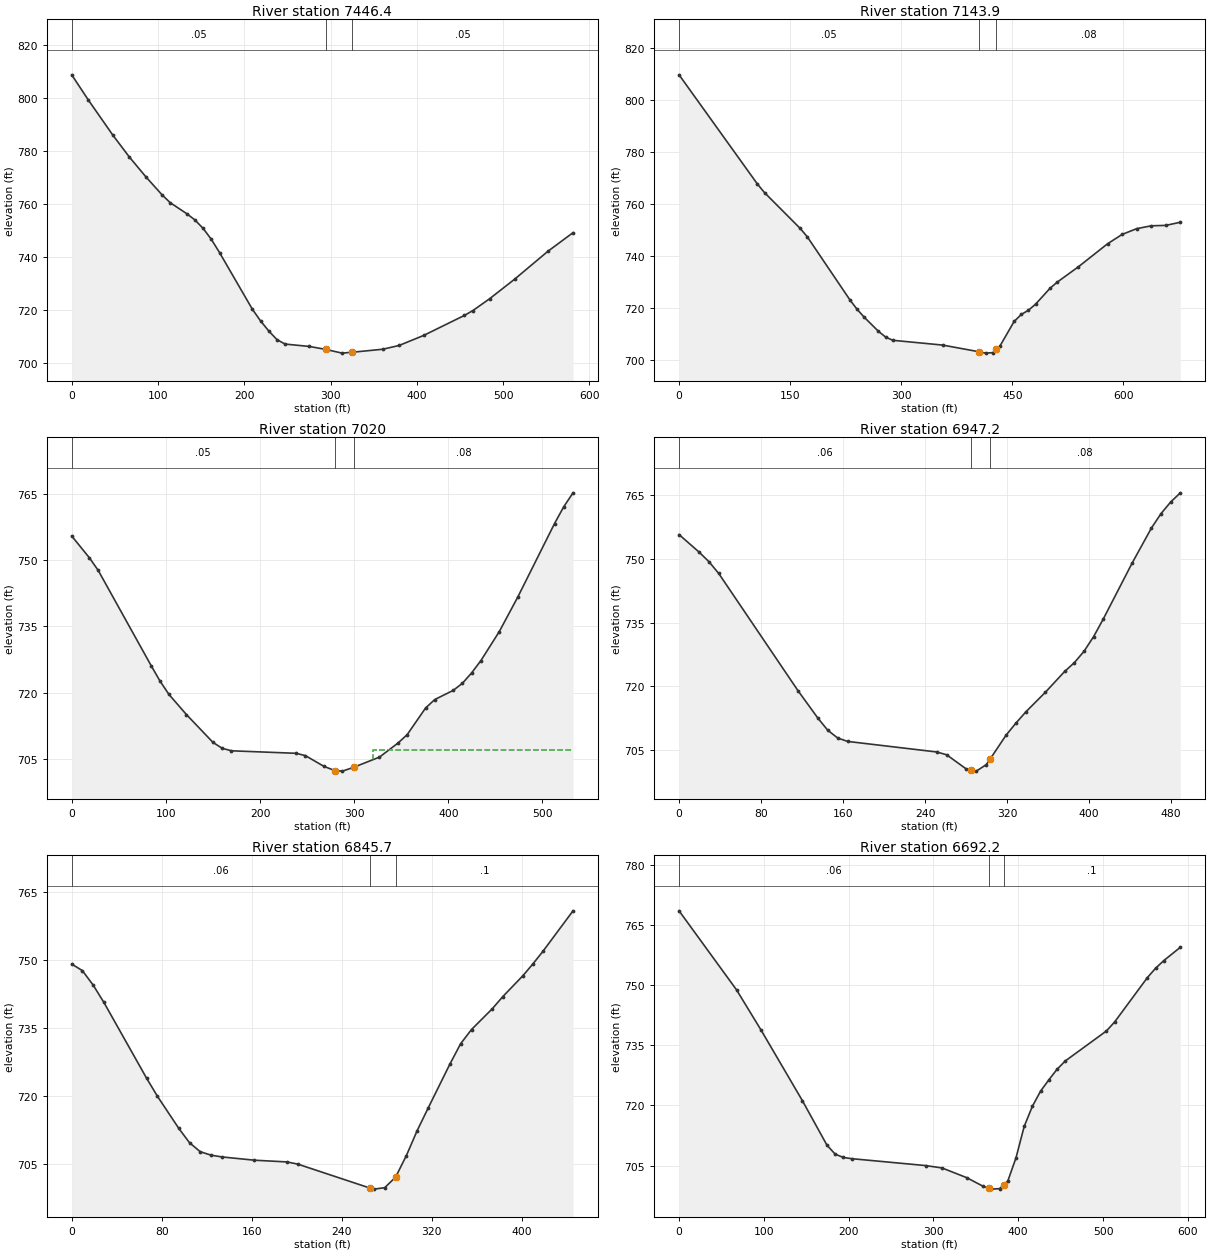
Type RM Length L Ch R = 1 ,7446.4  ,294.5,302.5,309.8
XS GIS Cut Line= 4
      1577201.72      365550.601     1577211.561      365769.282
     1577263.343      365989.839     1577259.879      366125.253
#Sta/Elev= 30
       0  808.65      19  799.28    47.6  785.94    66.6  777.75    85.7  770.29
   104.7  763.41   114.2  760.44   133.2  756.34   142.8  753.95   152.3  750.75
   161.8  746.64   171.3  741.65   209.4  720.26   218.9  715.87   228.3  712.12
   237.8  708.86   247.2  707.18   275.5  706.27   294.4  705.16   313.3  703.76
     325 704.085   360.5  705.23   379.4  706.65   407.7  710.41   455.1  717.98
   464.8  719.79   484.2  724.24   513.2  731.62   551.9  742.17   580.9  749.15
#Mann= 3 , 0 , 0
       0     .05       0   294.4    .045       0     325     .05       0
Bank Sta=294.4,325
XS Rating Curve= 0 ,0
Exp/Cntr=0.3,0.1

Type RM Length L Ch R = 1 ,7143.9  ,120.3,123.9,126.9
XS GIS Cut Line= 4
     1577049.601      365518.686     1576977.062      365767.957
     1576946.784      366045.874     1576970.435      366181.447
#Sta/Elev= 30
       0  809.78   105.8  767.67   115.4  764.36   163.5  750.58   173.1  747.34
   230.8  722.96   240.4  719.37     250  716.33   269.2   710.9   278.9  708.68
   288.5  707.44     356  705.59   404.9 703.018   413.8  702.49   423.5  702.67
   428.4 703.941   433.1  705.16   452.4  714.71     462  717.39   471.7  719.02
   481.3  721.36   500.6  727.41   510.2  729.78   539.2  735.79   578.5  744.64
   598.2  748.25   617.8  750.47   637.5  751.58   657.1  751.73   676.8  752.95
#Mann= 3 , 0 , 0
       0     .05       0   404.9    .045       0   428.4     .08       0
Bank Sta=404.9,428.4
XS Rating Curve= 0 ,0
Exp/Cntr=0.3,0.1

Type RM Length L Ch R = 1 ,7020    ,72.8,72.8,72.7
XS GIS Cut Line= 4
     1576914.489      365631.837      1576871.41      365775.585
     1576822.086      365965.729     1576654.072      366045.466
#Sta/Elev= 30
       0  755.45    18.8  750.51    28.1  747.68    84.4  726.11    93.8  722.63
   103.2  719.63   121.9  715.04   150.1  708.75   159.9  707.42   169.7  706.86
   238.5  706.29   248.3  705.76   267.9  703.34   279.5 702.384   287.6  702.26
   299.5 703.127   326.9  705.43   346.5   708.6   356.3   710.5   375.9  716.54
   385.6  718.45   405.2  720.52     415  722.13   424.8  724.48   434.6  727.25
   454.2  733.84   473.8  741.63   512.9  758.28   522.7  762.08   532.5  765.22
#Mann= 3 , 0 , 0
       0     .05       0   279.5    .045       0   299.5     .08       0
#XS Ineff= 2 , 0
       0                     320       0     707
Permanent Ineff=
       F       F
Bank Sta=279.5,299.5
XS Rating Curve= 0 ,0
Exp/Cntr=0.3,0.1

Type RM Length L Ch R = 1 ,6947.2  ,99.8,101.5,103.3
XS GIS Cut Line= 4
     1576854.593      365606.403     1576803.029      365752.259
     1576754.526       365939.24     1576646.259       366029.58
#Sta/Elev= 30
       0  755.68    19.3  751.61      29  749.35    38.7  746.54     116     719
   135.4  712.55     145  709.71   154.7  707.88   164.4  707.08   251.3   704.6
     261  703.94   280.3  700.57     285  700.34   289.9   700.1   299.6  701.62
   303.2 702.874   318.9  708.54   328.6   711.4   338.2  714.02   357.3  718.64
   376.1  723.53   385.5  725.58   394.9  728.24   404.3   731.7   413.7  735.83
   441.9     749   460.7  757.22   470.1  760.63   479.5  763.34   488.9  765.49
#Mann= 3 , 0 , 0
       0     .06       0     285    .045       0   303.2     .08       0
Bank Sta=285,303.2
XS Rating Curve= 0 ,0
Exp/Cntr=0.3,0.1

Type RM Length L Ch R = 1 ,6845.7  ,146.6,153.5,160.3
XS GIS Cut Line= 5
     1576804.723       365610.57     1576726.598      365693.903
     1576649.558      365922.289     1576639.922      365948.454
     1576640.877       366010.83
#Sta/Elev= 30
       0  749.08     9.5  747.62      19  744.46    28.6  740.62    66.6   723.9
    76.2  719.94    95.2  712.86   104.7  709.72   114.2  707.74   123.9  706.98
   133.5  706.59   162.4  705.87   191.4  705.49     201     705   265.4 699.703
   268.5   699.5   278.1  699.81   287.8  702.13   297.4  706.88     307  712.39
   316.7  717.33     336     727   345.6  731.52   355.3  734.66   373.8  739.24
   383.1  741.91     401  746.52   409.9  749.12   418.8  751.89   445.5   760.8
#Mann= 3 , 0 , 0
       0     .06       0   265.4    .045       0   287.8      .1       0
Bank Sta=265.4,287.8
XS Rating Curve= 0 ,0
Exp/Cntr=0.3,0.1

Type RM Length L Ch R = 1 ,6692.2  ,201,206.1,210.9
XS GIS Cut Line= 2
     1576762.868      365467.056     1576414.695      365944.839
#Sta/Elev= 30
       0   768.5    67.8   748.8    96.9  738.71   145.4  721.21   174.4  710.11
   184.1  707.87   193.8  707.04   203.5  706.74   290.8  705.02   310.1  704.43
   339.2  702.01   358.6  699.86   365.5  699.35   368.3  699.15     378  699.27
     383  700.25   387.7  701.17   397.4  706.97     407  714.76   416.7   719.8
   426.4  723.58   436.1  726.38   445.8  729.02   455.5  731.09     504  738.56
   513.6  740.78   552.4  751.88   562.1  754.22   571.8  756.12   591.2  759.42
#Mann= 3 , 0 , 0
       0     .06       0   365.5    .045       0     383      .1       0
Bank Sta=365.5,383
XS Rating Curve= 0 ,0
Exp/Cntr=0.3,0.1

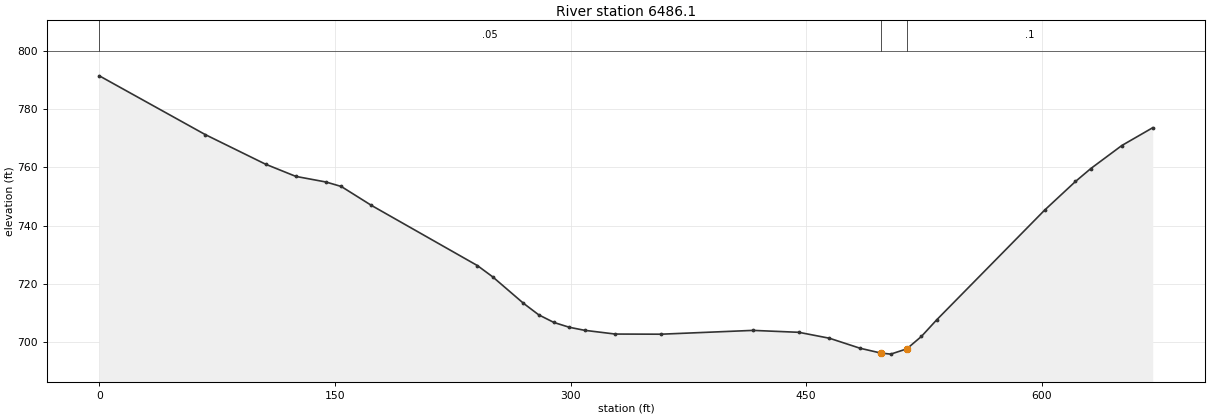
Type RM Length L Ch R = 1 ,6486.1  ,233.2,247.1,260.8
XS GIS Cut Line= 4
     1576802.613      365369.663     1576589.271      365458.096
     1576347.711       365670.38     1576296.681      365776.868
#Sta/Elev= 30
       0  791.48    67.4  771.29   105.8  761.11   125.1  756.91   144.3  754.98
     154  753.45   173.2  746.95   240.7  726.25   250.4  722.39   269.9  713.34
   279.7  709.33   289.4   706.7   299.2  705.05   308.9  704.01   328.4  702.72
   357.6  702.67   416.1  703.98   445.3  703.32   464.8  701.28   484.3  697.84
   497.6 696.178   503.8  695.82     514 697.623   523.3  701.88     533  707.57
   601.7  745.28   621.4  755.16   631.2  759.62   650.9  767.52   670.6  773.65
#Mann= 3 , 0 , 0
       0     .05       0   497.6    .045       0     514      .1       0
Bank Sta=497.6,514
XS Rating Curve= 0 ,0
Exp/Cntr=0.3,0.1