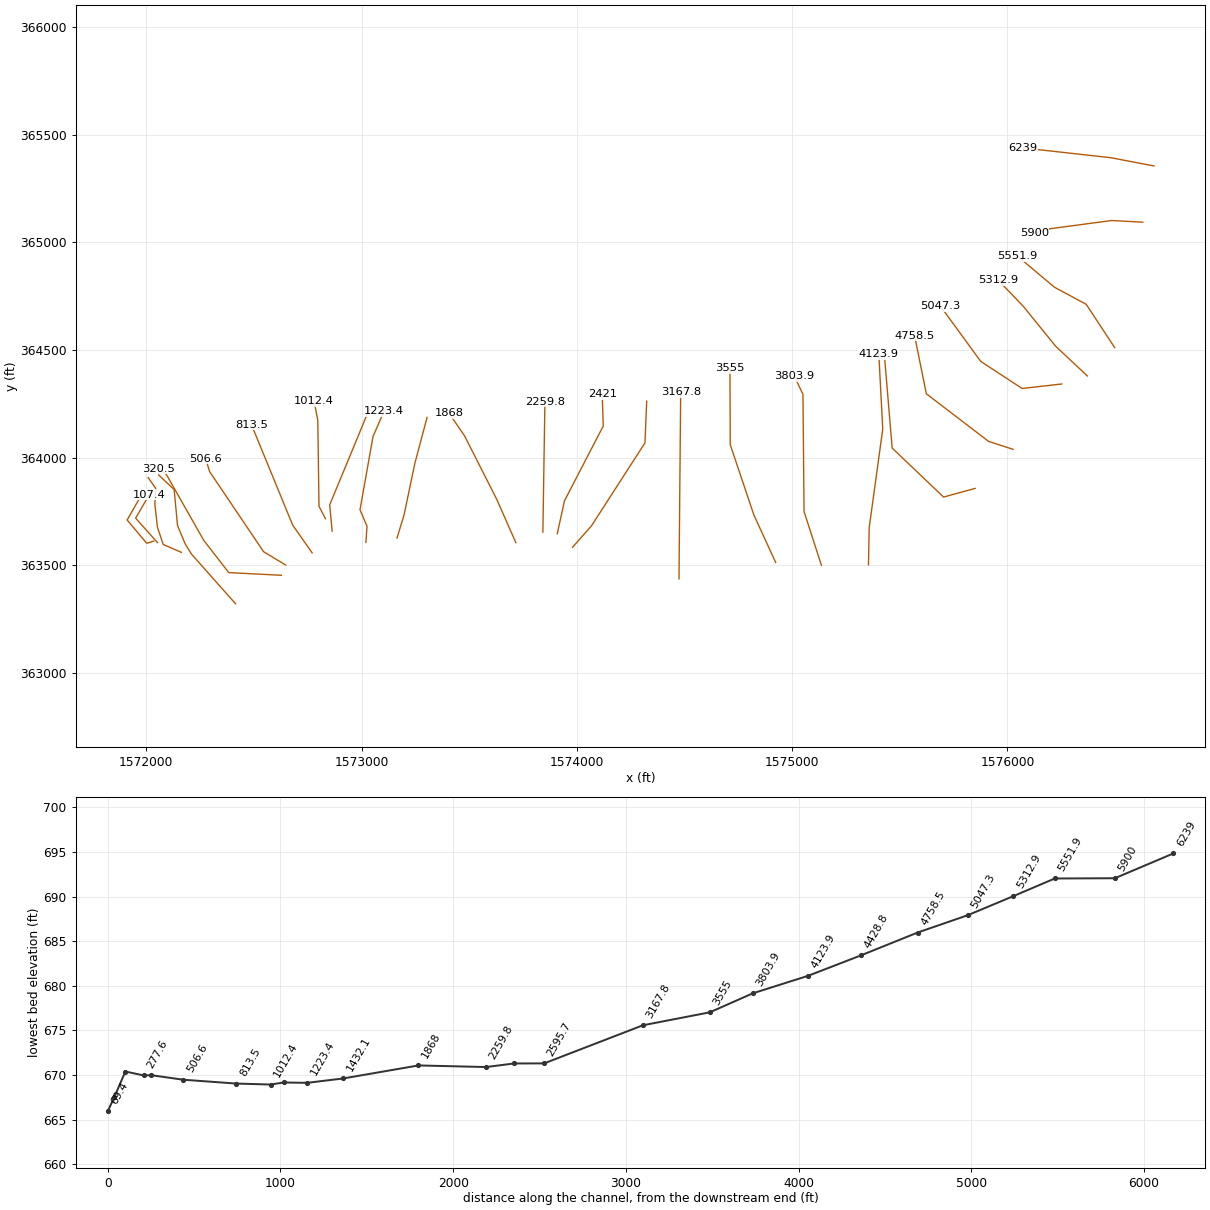
HEC-RAS study GORRLRN1.prj: GORRLRN1

--- GORRLRN1.g01 (geometry) --- (continued)

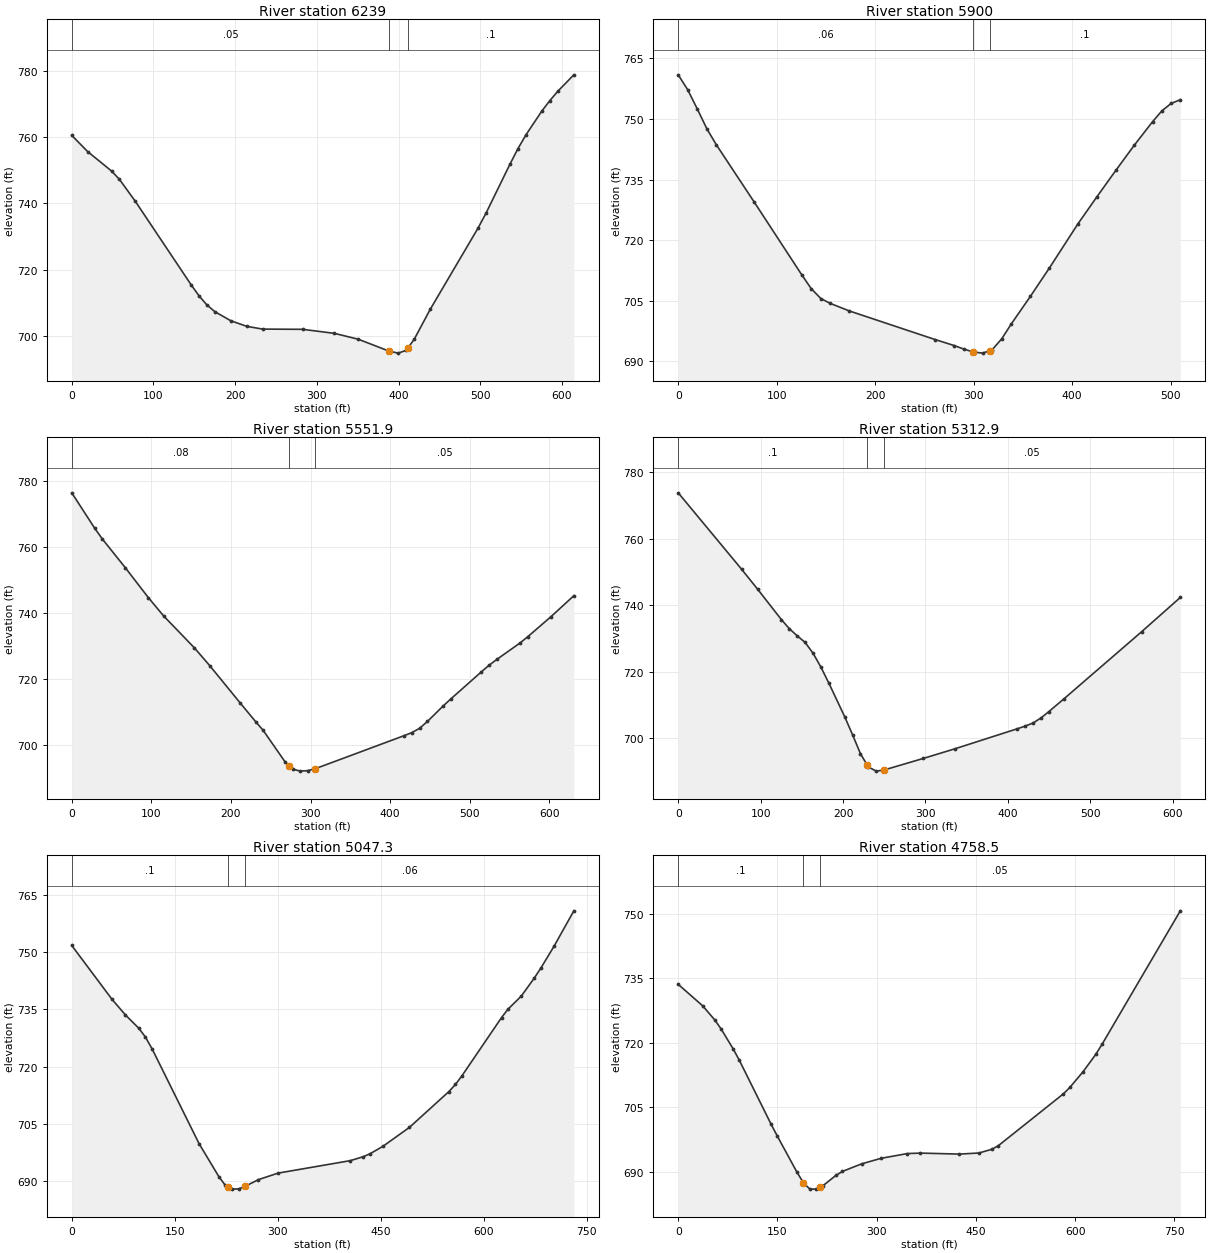
Type RM Length L Ch R = 1 ,6239    ,333.5,339,344.4
XS GIS Cut Line= 3
      1576680.96      365354.754     1576480.173      365393.121
     1576072.533      365438.531
#Sta/Elev= 30
       0   760.5    19.5  755.62    48.7  749.76    58.4  747.23    77.9  740.59
     146  715.48   155.8   712.1   165.5  709.35   175.2  707.33   194.7  704.59
   214.2  702.91   233.7  702.08   282.6  702.01   321.6  700.79   350.9  699.01
   388.6  695.41   399.7  694.83   409.5   695.7   411.6  696.42   419.3  699.06
   438.8  708.05   497.4  732.58   507.2  737.11   536.5  751.88   546.2  756.52
     556  760.68   575.5  767.88   585.3  771.03     595  773.83   614.6  778.78
#Mann= 3 , 0 , 0
       0     .05       0   388.6    .045       0   411.6      .1       0
Bank Sta=388.6,411.6
XS Rating Curve= 0 ,0
Exp/Cntr=0.3,0.1

Type RM Length L Ch R = 1 ,5900    ,362,348.1,333
XS GIS Cut Line= 4
      1576628.66      365093.599     1576484.124      365101.445
     1576196.381      365063.053     1576124.254      365042.894
#Sta/Elev= 30
       0  760.94     9.6  757.25    19.3  752.52      29  747.62    38.6  743.66
    77.2  729.43   125.4  711.45   135.1     708   144.8  705.57   154.4  704.36
   173.8  702.49   260.9  695.41   280.2  693.93   289.9  693.06   299.8 692.324
   309.2  692.05   316.3 692.664   318.8  692.88   328.6  695.62   338.3   699.3
   357.6  706.09     377  713.15     406  724.08   425.4  730.82   444.4  737.28
   463.1   743.5   481.8  749.36   491.2  752.03   500.6  753.86   509.9  754.78
#Mann= 3 , 0 , 0
       0     .06       0   299.8    .045       0   316.3      .1       0
Bank Sta=299.8,316.3
XS Rating Curve= 0 ,0
Exp/Cntr=0.3,0.1

Type RM Length L Ch R = 1 ,5551.9  ,247.9,239,230.6
XS GIS Cut Line= 4
     1576497.822      364511.471     1576365.522      364712.424
     1576217.917      364791.745     1576047.561      364935.125
#Sta/Elev= 30
       0  776.37    28.9   765.6    38.5  762.35    67.4  753.64    96.2  744.61
   115.5  739.03     154   729.4   173.2  724.03   211.7  712.65     231  707.02
   240.6  704.34   268.5  694.65     273  693.66   277.8  692.61   287.1  692.02
   296.4  692.16     306 692.759   417.8  702.79   427.5  703.72   437.2  705.04
   446.9  707.09   466.2  711.67   475.9  713.83   514.6  722.11   524.3  724.11
     534  725.88   563.1  730.84   572.7  732.72   601.8  738.77   630.8  745.19
#Mann= 3 , 0 , 0
       0     .08       0     273    .045       0     306     .05       0
Bank Sta=273,306
XS Rating Curve= 0 ,0
Exp/Cntr=0.3,0.1

Type RM Length L Ch R = 1 ,5312.9  ,258.6,265.6,272.6
XS GIS Cut Line= 4
     1576371.131      364379.555     1576223.724      364517.707
      1576073.81      364702.647     1575956.635      364824.596
#Sta/Elev= 27
       0  773.84      77   750.8    96.2  744.86   125.1  735.69   134.7  732.96
   144.3   730.8   153.9  728.82   163.6  725.54   173.2  721.33   182.8  716.52
     202  706.42   211.6  700.95   221.1  695.29   229.4  691.84   230.6  691.34
   240.1  690.05   249.4  690.37   297.2  693.86   335.4  696.75   411.5  702.81
     421  703.61   430.6  704.55   440.1  706.06   449.5  707.93   468.3  711.88
   562.2  732.01   609.2  742.34
#Mann= 3 , 0 , 0
       0      .1       0   229.4    .045       0   249.4     .05       0
Bank Sta=229.4,249.4
XS Rating Curve= 0 ,0
Exp/Cntr=0.3,0.1

Type RM Length L Ch R = 1 ,5047.3  ,290.2,288.8,287.1
XS GIS Cut Line= 4
     1576252.349      364342.256     1576068.165      364321.321
     1575876.006      364446.931     1575689.836      364702.182
#Sta/Elev= 30
       0  751.74    58.5  737.65      78  733.56    97.6  730.05   107.3  727.73
   117.1  724.59   185.4  699.79   214.1  691.18   223.6  688.88   227.6  688.47
   233.2   687.9   242.8  687.96     252 688.599   271.5  690.37   300.2  692.09
   405.4  695.36   424.5  696.41   434.1  697.16   453.2  699.14   491.5  704.07
     549  713.46   558.6  715.34   568.1  717.62   625.6  732.84   635.1  735.06
   654.3  738.46   673.4  743.22     683  745.86   702.2  751.58   730.9  760.82
#Mann= 3 , 0 , 0
       0      .1       0   227.6    .045       0     252     .06       0
Bank Sta=227.6,252
XS Rating Curve= 0 ,0
Exp/Cntr=0.3,0.1

Type RM Length L Ch R = 1 ,4758.5  ,331.8,329.8,326.9
XS GIS Cut Line= 4
      1576026.54      364038.597     1575912.141      364075.643
     1575623.251      364296.798     1575568.728      364566.375
#Sta/Elev= 30
       0   733.6      37   728.6    55.5  725.27    64.8  723.23    83.2  718.55
    92.5   715.9   139.9  701.22   149.8   698.3   179.2     690   189.1  687.47
   198.9  685.99   208.8  685.97   214.1 686.388   218.6  686.74   238.2  689.14
   248.1  690.08   277.6  691.87   307.1  693.15   346.4  694.24   366.1  694.35
   425.1  694.12   454.6  694.37   474.2  695.24   484.1  696.09   582.3  708.13
   592.1  709.63   611.8  713.22   631.4  717.34   641.2  719.77   759.1   750.7
#Mann= 3 , 0 , 0
       0      .1       0   189.1    .045       0   214.1     .05       0
Bank Sta=189.1,214.1
XS Rating Curve= 0 ,0
Exp/Cntr=0.3,0.1

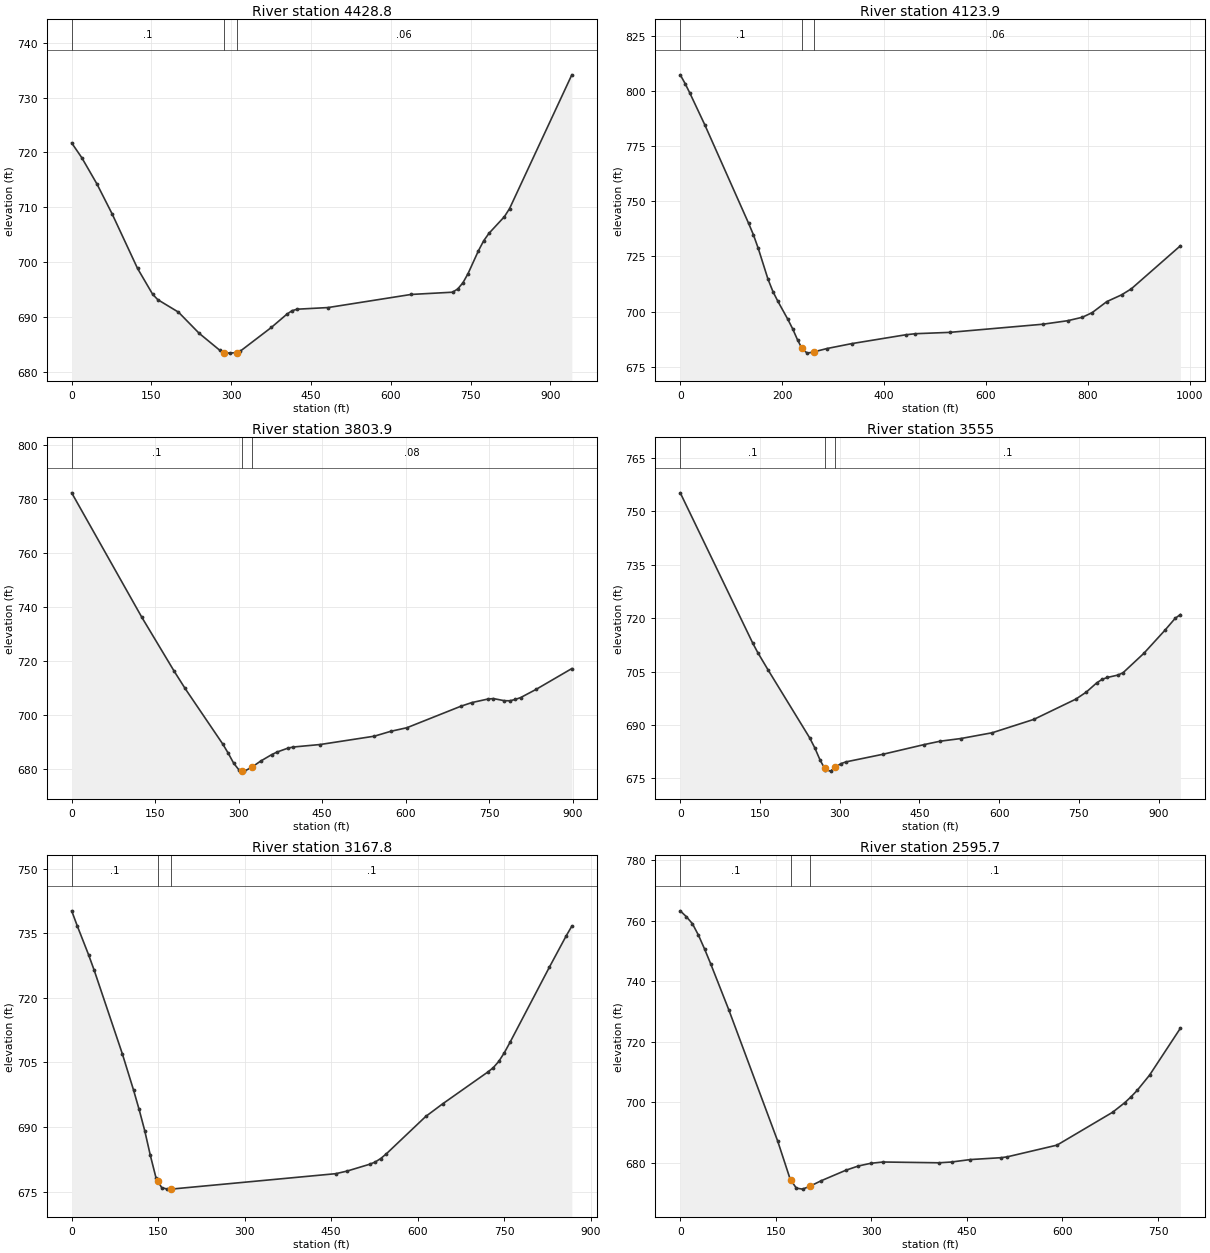
Type RM Length L Ch R = 1 ,4428.8  ,325.6,304.8,282.7
XS GIS Cut Line= 4
     1575849.978      363857.174     1575703.052       363817.05
     1575464.533       364044.56     1575426.366      364501.271
#Sta/Elev= 30
       0  721.73      19  719.04    47.6  714.23    76.2  708.76   123.8  698.85
   152.3  694.12     162  693.14   200.8  690.87   239.6  687.02   278.3  683.93
     287 683.509   297.7   683.4     310  683.51   317.1  683.77   375.3  688.08
   404.4  690.49   414.1  691.13   423.8  691.41   481.9  691.71     638   694.1
     716  694.51   725.7   695.1   735.5  696.23   745.2  697.92   764.7  702.08
   774.5  703.88   784.2  705.22   813.5  708.29   823.2  709.77   940.2  734.15
#Mann= 3 , 0 , 0
       0      .1       0     287    .045       0     310     .06       0
Bank Sta=287,310
XS Rating Curve= 0 ,0
Exp/Cntr=0.3,0.1

Type RM Length L Ch R = 1 ,4123.9  ,317,320.1,323.5
XS GIS Cut Line= 4
     1575354.491      363502.399     1575357.855      363674.708
     1575420.847      364133.215     1575402.618       364479.57
#Sta/Elev= 30
       0  807.38     9.6   803.4    19.2  798.92    47.9  784.84     134  740.12
   143.6  734.84   153.2   728.6   172.3  714.65     182  709.04   191.6  704.66
   210.9   696.6   220.6   692.2   230.2  687.18   238.6  683.41   239.8  682.87
   249.5  681.12   262.6 681.703     288   683.2   336.3  685.42   442.3  689.43
   461.6  689.93   529.1  690.54   712.2  694.24   760.4  695.82   789.3  697.38
   808.6  699.47   837.5   704.5   866.4  707.55   885.6  710.29     982  729.83
#Mann= 3 , 0 , 0
       0      .1       0   238.6    .045       0   262.6     .06       0
Bank Sta=238.6,262.6
XS Rating Curve= 0 ,0
Exp/Cntr=0.3,0.1

Type RM Length L Ch R = 1 ,3803.9  ,241.8,248.9,256.1
XS GIS Cut Line= 4
     1575135.836       363500.61     1575055.335      363749.661
     1575050.144      364294.154     1575010.836      364377.346
#Sta/Elev= 30
       0  782.33     126  736.19   184.2  716.17   203.6  709.84   271.5  689.16
   281.2   685.8   290.9  682.12   300.6  679.57   305.1 679.382   310.4  679.16
   323.1 680.553   339.5  682.89     359  685.25   368.7  686.22   388.1  687.66
   397.9   688.1   446.5  689.03   543.7  692.12   572.9  693.91   602.1  695.25
   699.3  703.24   718.7  704.57   747.9   705.9   757.6  706.05   777.1  705.27
   786.8  705.24   796.5  705.72   806.3  706.42   833.9  709.44   898.3  717.18
#Mann= 3 , 0 , 0
       0      .1       0   305.1    .045       0   323.1     .08       0
Bank Sta=305.1,323.1
XS Rating Curve= 0 ,0
Exp/Cntr=0.3,0.1

Type RM Length L Ch R = 1 ,3555    ,394.1,387.2,378.8
XS GIS Cut Line= 4
     1574923.451      363513.424     1574821.889      363734.778
     1574712.514      364060.299     1574711.212      364414.465
#Sta/Elev= 30
       0   755.2   136.4  712.98   146.1  710.26   165.6  705.37   243.5  686.38
   253.4  683.49   263.2   680.1   271.6 677.846     273  677.47   282.8  677.03
   291.6 678.126   302.4  679.14   312.2  679.64   380.9  681.75   459.4   684.5
   488.8  685.43   528.1  686.19     587  687.81   665.6  691.58   744.4  697.26
     764  699.23   783.7  701.83   793.5  702.78   803.4  703.33   823.1     704
   832.9  704.63   872.2   710.1   911.6  716.54   931.3  719.96   941.1  721.02
#Mann= 3 , 0 , 0
       0      .1       0   271.6    .045       0   291.6      .1       0
Bank Sta=271.6,291.6
XS Rating Curve= 0 ,0
Exp/Cntr=0.3,0.1

Type RM Length L Ch R = 1 ,3167.8  ,534.6,572.1,541.2
XS GIS Cut Line= 2
     1574474.493      363437.295     1574482.305      364304.353
#Sta/Elev= 30
       0  740.23     9.7  736.73    29.2  730.06      39  726.44    87.7  707.07
   107.2  698.62   116.9   694.1   126.6  689.19   136.4   683.4   146.1  678.26
     149 677.578   155.9  675.95   165.6  675.58   172.9  675.59   457.9  679.17
   477.4  679.77   516.4  681.35   526.1  681.87   535.8  682.69   545.6  683.79
   613.8  692.46     643  695.38     721  702.74   730.7  703.77   740.4  705.24
   750.2  707.29   759.9  709.67   828.1  727.12   857.4  734.43   867.1  736.67
#Mann= 3 , 0 , 0
       0      .1       0     149    .045       0   172.9      .1       0
Bank Sta=149,172.9
XS Rating Curve= 0 ,0
Exp/Cntr=0.3,0.1

Type RM Length L Ch R = 1 ,2595.7  ,172.5,174.7,176.8
XS GIS Cut Line= 4
     1573979.918      363583.693     1574068.281      363683.808
     1574316.411      364068.621     1574324.536      364262.122
#Sta/Elev= 30
       0  763.34     9.5  761.42    19.1  759.09    28.6  755.27    38.2   750.7
    47.7  745.85    76.3  730.55     153  687.17   172.5  674.63   173.2 674.414
   182.2  671.64     192  671.31   203.7 672.285   221.2  674.08   260.2  677.58
   279.7  678.97   299.2  679.86   318.6  680.28   406.3  680.02   425.8  680.28
     455  681.08   503.7  681.71   513.5     682   591.4  685.86   678.6  696.72
   697.9  699.92   707.6  701.84   717.3  703.98   736.7  709.01   785.1  724.53
#Mann= 3 , 0 , 0
       0      .1       0   173.2    .045       0   203.7      .1       0
Bank Sta=173.2,203.7
XS Rating Curve= 0 ,0
Exp/Cntr=0.3,0.1

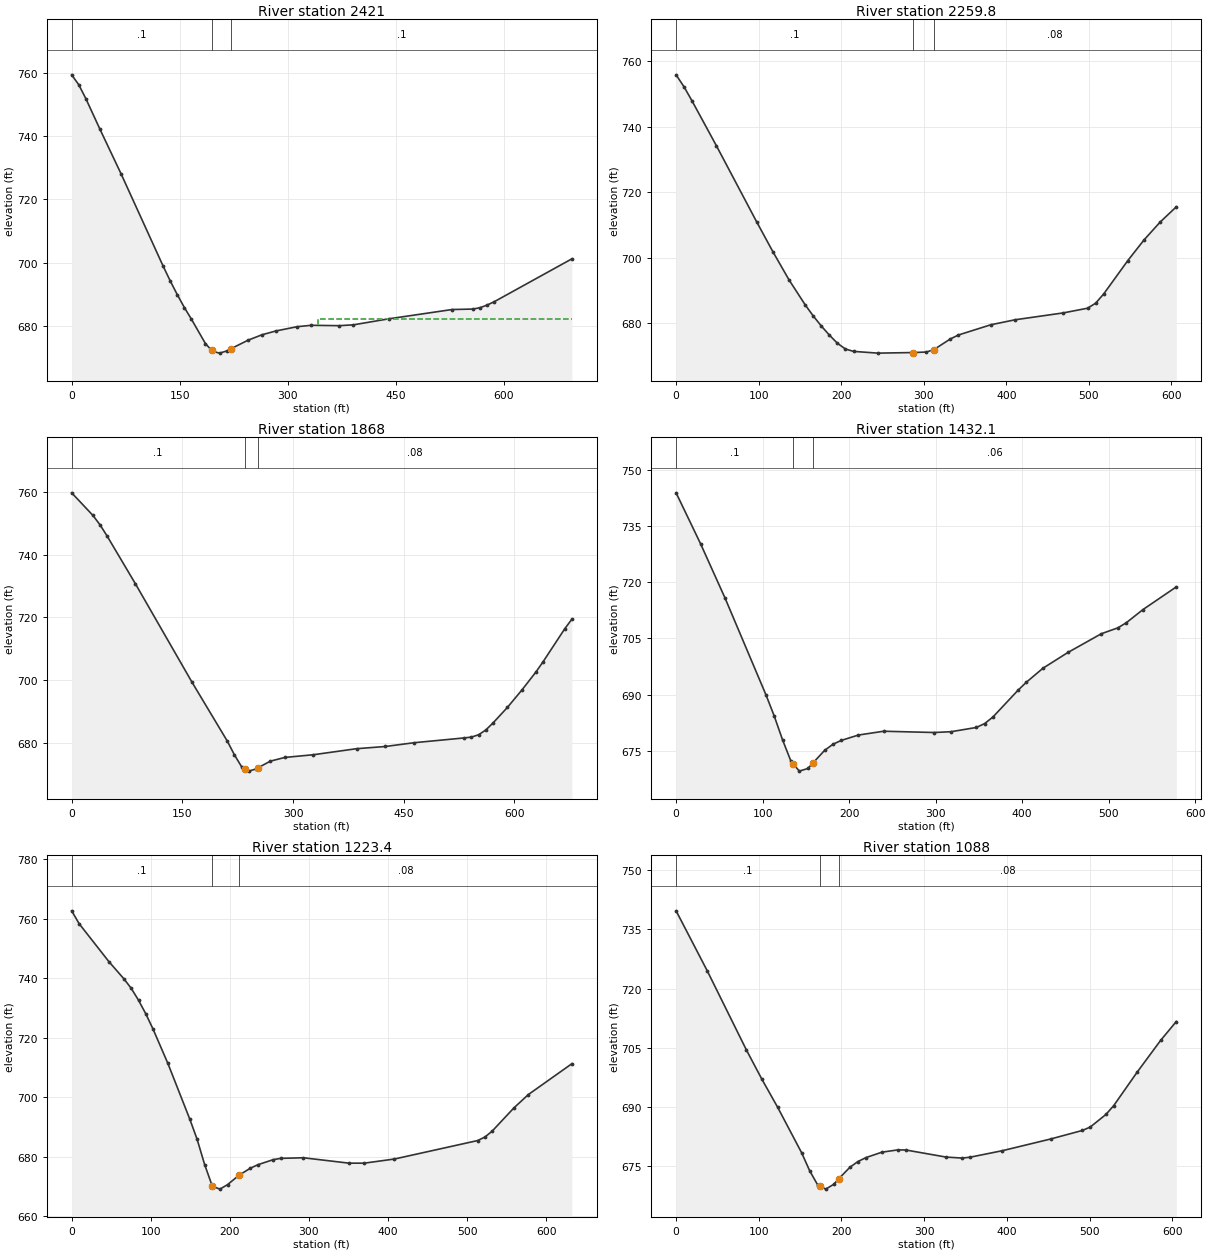
Type RM Length L Ch R = 1 ,2421    ,147.5,161.1,171.2
XS GIS Cut Line= 4
       1573909.1      363646.906     1573942.599      363799.643
     1574122.642      364146.906     1574117.867      364293.607
#Sta/Elev= 30
       0  759.51     9.8  756.38    19.6     752    39.1  742.34    68.4  728.21
     127  698.85   136.8  694.19   146.6  689.82   156.4  685.76   166.2  682.06
   185.7  674.31   194.1  672.22   195.5  671.87   205.3   671.3     215  671.97
   221.1 672.692   244.4  675.36   263.9   677.1   283.5  678.33   312.8  679.67
   332.4  680.12   371.5     680   391.1  680.27     440  682.17     528  685.12
   557.3  685.27   567.1  685.73   576.9  686.56   586.7  687.62   694.3  701.19
#Mann= 3 , 0 , 0
       0      .1       0   194.1    .045       0   221.1      .1       0
#XS Ineff= 2 , 0
       0                     342       0     682
Permanent Ineff=
       F       F
Bank Sta=194.1,221.1
XS Rating Curve= 0 ,0
Exp/Cntr=0.3,0.1

Type RM Length L Ch R = 1 ,2259.8  ,379,391.9,399.5
XS GIS Cut Line= 2
      1573842.26       363654.14     1573851.808      364260.043
#Sta/Elev= 30
       0  755.84     9.8   752.1    19.6  747.74    48.9  734.16    97.7  710.92
   117.3  701.83   136.8  693.26   156.4  685.63   166.2  682.23   175.9  679.18
   185.7   676.4   195.5  673.89   205.2  672.15     215  671.43   244.4   670.9
   287.5  671.08     303  671.23     312 671.928   332.3  675.24   342.1  676.44
   381.2  679.55   410.5  681.07   469.1  683.18   498.5  684.61   508.2  686.13
     518  688.96   547.3  699.17   566.9  705.46   586.4   710.9     606  715.56
#Mann= 3 , 0 , 0
       0      .1       0   287.5    .045       0     312     .08       0
Bank Sta=287.5,312
XS Rating Curve= 0 ,0
Exp/Cntr=0.3,0.1

Type RM Length L Ch R = 1 ,1868    ,450.5,435.9,420.2
XS GIS Cut Line= 4
     1573716.723      363605.264     1573627.747      363807.087
     1573478.008      364102.225     1573406.393      364206.392
#Sta/Elev= 30
       0  759.67    28.8  752.48    38.4  749.49      48  745.92    86.3  730.75
     163  699.41     211   680.6   220.6  676.25   230.3  672.46   234.5 671.862
     240  671.08   249.8  671.78   252.5 672.141   269.2  674.25   288.7  675.43
   327.6   676.3     386  678.22     425  678.92   463.9  680.12     532  681.65
   541.8  681.92   551.5  682.66   561.2  684.17     571  686.41   590.4  691.34
   609.9  696.83   629.3  702.68     639  705.95   668.2  716.39   677.9  719.46
#Mann= 3 , 0 , 0
       0      .1       0   234.5    .045       0   252.5     .08       0
Bank Sta=234.5,252.5
XS Rating Curve= 0 ,0
Exp/Cntr=0.3,0.1

Type RM Length L Ch R = 1 ,1432.1  ,207.8,208.7,209.1
XS GIS Cut Line= 4
     1573164.706      363626.488     1573197.731        363734.9
     1573247.585      363973.099     1573304.462      364187.252
#Sta/Elev= 30
       0  743.84    28.3  730.25    56.7  715.71   103.9  689.96   113.3  684.41
   123.1  677.94   132.8  672.24   135.1  671.62   142.5  669.62   152.3  670.33
   158.6  671.89   171.7  675.16   181.5  676.81   191.2  677.83   210.7  679.24
   239.9  680.26   298.3  679.92   317.8  680.13     347  681.26   356.7   682.3
   366.3  684.06   395.2  691.17   404.9  693.32   424.1  697.06     453  701.27
   491.6  706.26   510.8  707.84   520.5   709.2   539.7   712.7   578.3  718.76
#Mann= 3 , 0 , 0
       0      .1       0   135.1    .045       0   158.6     .06       0
Bank Sta=135.1,158.6
XS Rating Curve= 0 ,0
Exp/Cntr=0.3,0.1

Type RM Length L Ch R = 1 ,1223.4  ,140.1,135.4,130.4
XS GIS Cut Line= 5
     1573020.283      363606.219     1573025.491      363681.306
     1572992.906      363758.014     1573053.398       364098.15
      1573104.44      364215.859
#Sta/Elev= 30
       0  762.65     9.4  758.34      47   745.6    65.9  739.84    75.3   736.6
    84.5  732.61    93.8     728     103  722.83   121.6  711.39   149.4   692.6
   158.6  685.86   168.2   677.3   177.8  670.12   187.4  669.13     197  670.63
   211.5  673.79   225.8  676.15   235.4  677.33   254.6  679.02   264.2  679.47
     293  679.67   350.5  677.86   369.7  677.85   408.1  679.25   513.2  685.45
   522.4  686.62   531.6  688.62   559.1  696.43   577.4  700.92   632.4  711.28
#Mann= 3 , 0 , 0
       0      .1       0   177.8    .045       0   211.5     .08       0
Bank Sta=177.8,211.5
XS Rating Curve= 0 ,0
Exp/Cntr=0.3,0.1

Type RM Length L Ch R = 1 ,1088    ,66.2,75.7,84.8
XS GIS Cut Line= 4
     1572863.381      363659.001      1572852.27      363781.223
      1572989.77      364113.168     1573036.297      364227.057
#Sta/Elev= 30
       0   739.7    37.8  724.44      85  704.45   103.8     697   122.7  689.96
   151.9  678.35   161.6   673.8   171.3  670.21   173.9 669.931     181  669.17
   190.7   670.4   196.9 671.832   210.1  674.69   219.8  676.15   229.5  677.15
     249  678.54   268.4  679.12   278.1  679.08   326.6  677.29   346.1  677.04
   355.8  677.27   394.6  678.91   452.9  681.87   491.5  684.05     501  684.92
   519.9   688.1   529.3  690.34   557.7  698.84   586.1  706.89     605  711.65
#Mann= 3 , 0 , 0
       0      .1       0   173.9    .045       0   196.9     .08       0
Bank Sta=173.9,196.9
XS Rating Curve= 0 ,0
Exp/Cntr=0.3,0.1

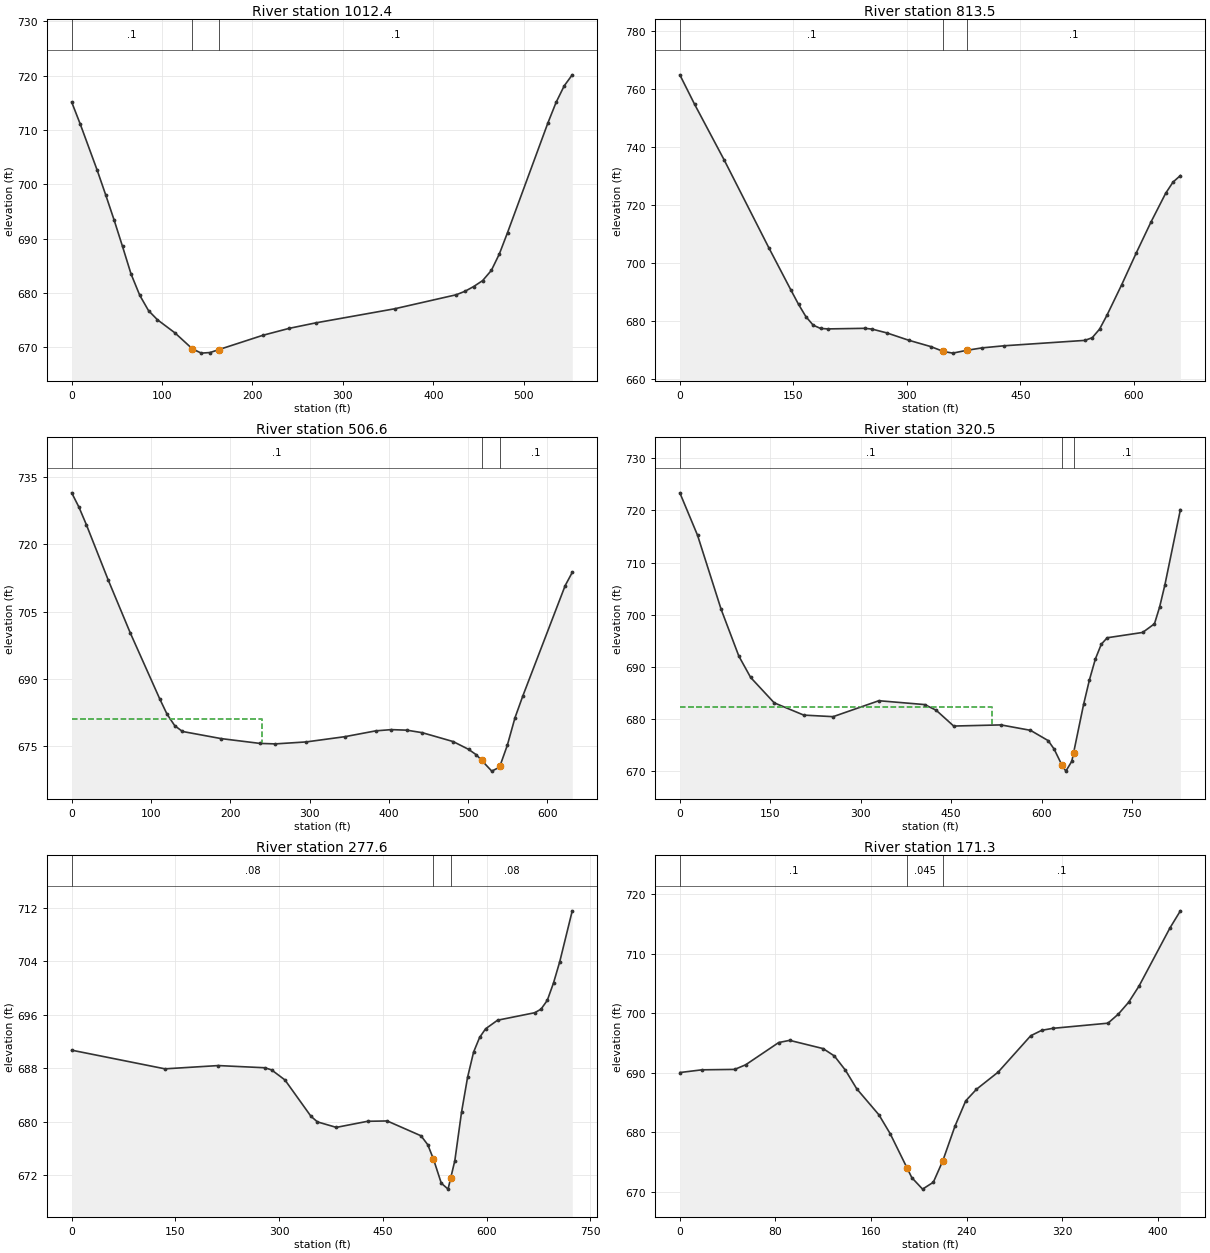
Type RM Length L Ch R = 1 ,1012.4  ,189.3,198.8,209.9
XS GIS Cut Line= 4
     1572832.425      363716.114     1572802.467      363774.455
     1572796.914      364173.011     1572780.056       364260.93
#Sta/Elev= 30
       0  715.14     9.4  711.12    28.1  702.65    37.5  698.12    46.8   693.5
    56.2  688.59    65.6  683.53    75.3  679.58      85  676.76    94.8  675.09
   114.2  672.67   133.6  669.71   143.4  668.94   153.1  669.05   162.8  669.59
   211.4  672.22   240.6   673.5   269.7   674.5   357.2   677.1   425.3  679.68
     435  680.32   444.7   681.2   454.5  682.28   464.2  684.16   473.1  687.21
   482.1  691.12   526.8  711.32   535.8  715.08   544.8  718.13   553.7  720.16
#Mann= 3 , 0 , 0
       0      .1       0   133.6    .045       0   162.8      .1       0
Bank Sta=133.6,162.8
XS Rating Curve= 0 ,0
Exp/Cntr=0.3,0.1

Type RM Length L Ch R = 1 ,813.5   ,303,307,308.6
XS GIS Cut Line= 3
     1572770.554      363557.976     1572680.415      363686.317
     1572488.901      364153.094
#Sta/Elev= 30
       0  764.88    19.6  754.69    58.8  735.46   117.6  705.33     147  690.66
   156.8  685.88   166.5  681.64   176.2  678.68   185.9  677.55   195.6  677.39
   244.2  677.59   253.9  677.33   273.3  676.03   302.4  673.49   331.5  671.31
   348.3 669.622   360.6  669.05   378.8 670.005   399.4  670.86   428.5  671.58
   535.2  673.44   544.9  674.36   554.6  677.31   564.3  682.06   583.8  692.58
   603.2  703.61   622.6  714.22     642  724.11   651.7  727.96   661.4  730.19
#Mann= 3 , 0 , 0
       0      .1       0   348.3    .045       0   378.8      .1       0
Bank Sta=348.3,378.8
XS Rating Curve= 0 ,0
Exp/Cntr=0.3,0.1

Type RM Length L Ch R = 1 ,506.6   ,187.7,186,184.2
XS GIS Cut Line= 4
     1572647.844      363501.206     1572544.979      363563.445
     1572294.253      363935.482     1572276.309       363995.26
#Sta/Elev= 30
       0  731.51     9.2   728.3    18.5  724.41    46.2  712.02      74  700.24
     111   685.6   120.2  682.19     130   679.6   139.7  678.32   188.5  676.73
   237.3  675.66   256.8  675.55   295.8  675.99   344.6  677.16   383.6  678.46
   403.1  678.73   422.6  678.61   442.1  678.05   481.1  676.07   500.6  674.33
   510.4  673.11   517.2 671.855   529.8  669.48   539.6  670.36   540.2 670.659
   549.4  675.24   559.1  681.39   568.9  686.21   622.4  710.84   631.3  713.78
#Mann= 3 , 0 , 0
       0      .1       0   517.2    .045       0   540.2      .1       0
#XS Ineff= 2 , 0
       0     240     681               0
Permanent Ineff=
       F       F
Bank Sta=517.2,540.2
XS Rating Curve= 0 ,0
Exp/Cntr=0.3,0.1

Type RM Length L Ch R = 1 ,320.5   ,52.7,43,30.9
XS GIS Cut Line= 5
     1572627.685       363453.72     1572383.241       363466.22
      1572266.89      363616.399     1572092.914      363923.137
     1572058.935      363949.554
#Sta/Elev= 30
       0  723.39    29.4  715.24    68.5  701.04    97.9  692.06   117.5  687.96
   156.6  683.09   205.6  680.74   254.3  680.44   330.2   683.5   406.2  682.76
   425.2  681.68   454.3  678.64   532.7  678.86   581.7  677.82   611.1  675.84
   620.9  674.23   633.7 671.186   640.4  669.99   650.2  671.87   653.2 673.485
   669.8  682.78   679.6  687.54   689.4  691.52   699.2  694.34     709  695.58
   767.8   696.6   787.4  698.26     796   701.5   804.6  705.68   830.4  720.17
#Mann= 3 , 0 , 0
       0      .1       0   633.7    .045       0   653.2      .1       0
#XS Ineff= 2 , 0
          518.16  682.23
Permanent Ineff=
       F       F
Bank Sta=633.7,653.2
XS Rating Curve= 0 ,0
Exp/Cntr=0.3,0.1

Type RM Length L Ch R = 1 ,277.6   ,106.6,106.3,106
XS GIS Cut Line= 6
     1572414.852       363321.38     1572210.273      363552.113
     1572180.669      363600.188     1572145.406      363684.583
     1572129.781      363851.683     1572057.544      363919.787
#Sta/Elev= 30
       0  690.73   134.9  687.94     212  688.43   279.5   688.1   289.1  687.78
   308.4  686.28     346  680.85   355.4  680.01   382.7  679.19   427.9   680.1
   456.3  680.15   505.2  677.93     515  676.59   523.2 674.443   534.5  670.85
   544.3  669.96   548.2 671.656   554.1  674.22   563.8  681.47   572.5  686.66
   581.2  690.44   589.9  692.63   598.6  693.93   615.9  695.21   669.7  696.33
   678.8  696.87   687.8  698.18   696.8  700.78   705.8  703.95   723.9  711.56
#Mann= 3 , 0 , 0
       0     .08       0   523.2    .045       0   548.2     .08       0
Bank Sta=523.2,548.2
XS Rating Curve= 0 ,0
Exp/Cntr=0.3,0.1

Type RM Length L Ch R = 1 ,171.3   ,48.3,63.9,80.3
XS GIS Cut Line= 6
     1572163.308      363560.258     1572078.993      363596.733
     1572052.263       363676.51     1572040.111      363784.149
     1572044.017      363857.933     1572008.933      363907.287
#Sta/Elev= 30
       0  690.02    18.4  690.48    45.9  690.55    55.1  691.33    82.7  695.07
    91.9  695.44   119.9  694.05   129.3  692.81   138.6   690.4     148  687.29
   166.6   682.9     176  679.73     190 674.006   194.1  672.33   203.1   670.4
   212.1  671.56     220 675.158   230.2     681   239.2  685.26   248.2  687.21
   266.3  690.09   293.6  696.22   302.8  697.13     312  697.46   358.2  698.33
   366.9  699.86   375.5  701.85   384.2  704.58   410.1  714.37   418.8  717.24
#Mann= 3 , 0 , 0
       0      .1       0     190    .045       0     220      .1       0
Bank Sta=190,220
XS Rating Curve= 0 ,0
Exp/Cntr=0.3,0.1

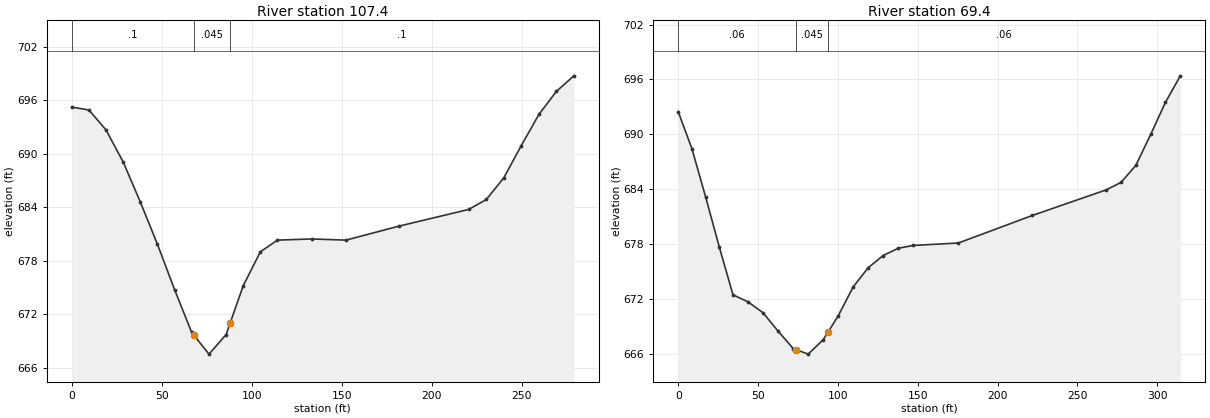
Type RM Length L Ch R = 1 ,107.4   ,38.7,38,37.3
XS GIS Cut Line= 3
     1572052.336       363605.55     1571950.773      363719.092
     1572014.315      363828.467
#Sta/Elev= 25
       0  695.24     9.5  694.92      19  692.69    28.6  689.06    38.1  684.58
    47.6  679.84    57.1  674.76    66.6  669.96    67.9  669.63    76.2  667.53
    85.7  669.72    87.9  670.99    95.2   675.2   104.7     679   114.2  680.32
   133.3  680.45   152.3  680.32   181.5  681.88   220.4  683.76   230.2  684.88
   239.9  687.31   249.6  690.92   259.4  694.42   269.1     697   278.8  698.75
#Mann= 3 , 0 , 0
       0      .1       0    67.9    .045       0    87.9      .1       0
Bank Sta=67.9,87.9
XS Rating Curve= 0 ,0
Exp/Cntr=0.3,0.1

Type RM Length L Ch R = 1 ,69.4    ,69.6,69.4,69.1
XS GIS Cut Line= 4
     1572035.148      363612.321     1572002.318      363602.411
     1571911.399      363710.496     1571980.461      363831.071
#Sta/Elev= 27
       0  692.47     8.6  688.41    17.2  683.12    25.7  677.68    34.3  672.44
    43.7  671.67    53.1  670.48    62.5  668.48      72  666.56    73.8 666.443
    81.4  665.95    90.8  667.53    93.8  668.36   100.2  670.13   109.6  673.31
     119  675.41   128.4  676.74   137.9  677.54   147.3  677.84   175.5  678.11
   221.8  681.12   268.2  683.93   277.4  684.74   286.7  686.62     296  690.01
   305.2   693.5   314.5   696.4
#Mann= 3 , 0 , 0
       0     .06       0    73.8    .045       0    93.8     .06       0
Bank Sta=73.8,93.8
XS Rating Curve= 0 ,0
Exp/Cntr=0.3,0.1

Chan Stop Cuts=-1
Use User Specified Reach Order=0
Composite Channel Slope=5